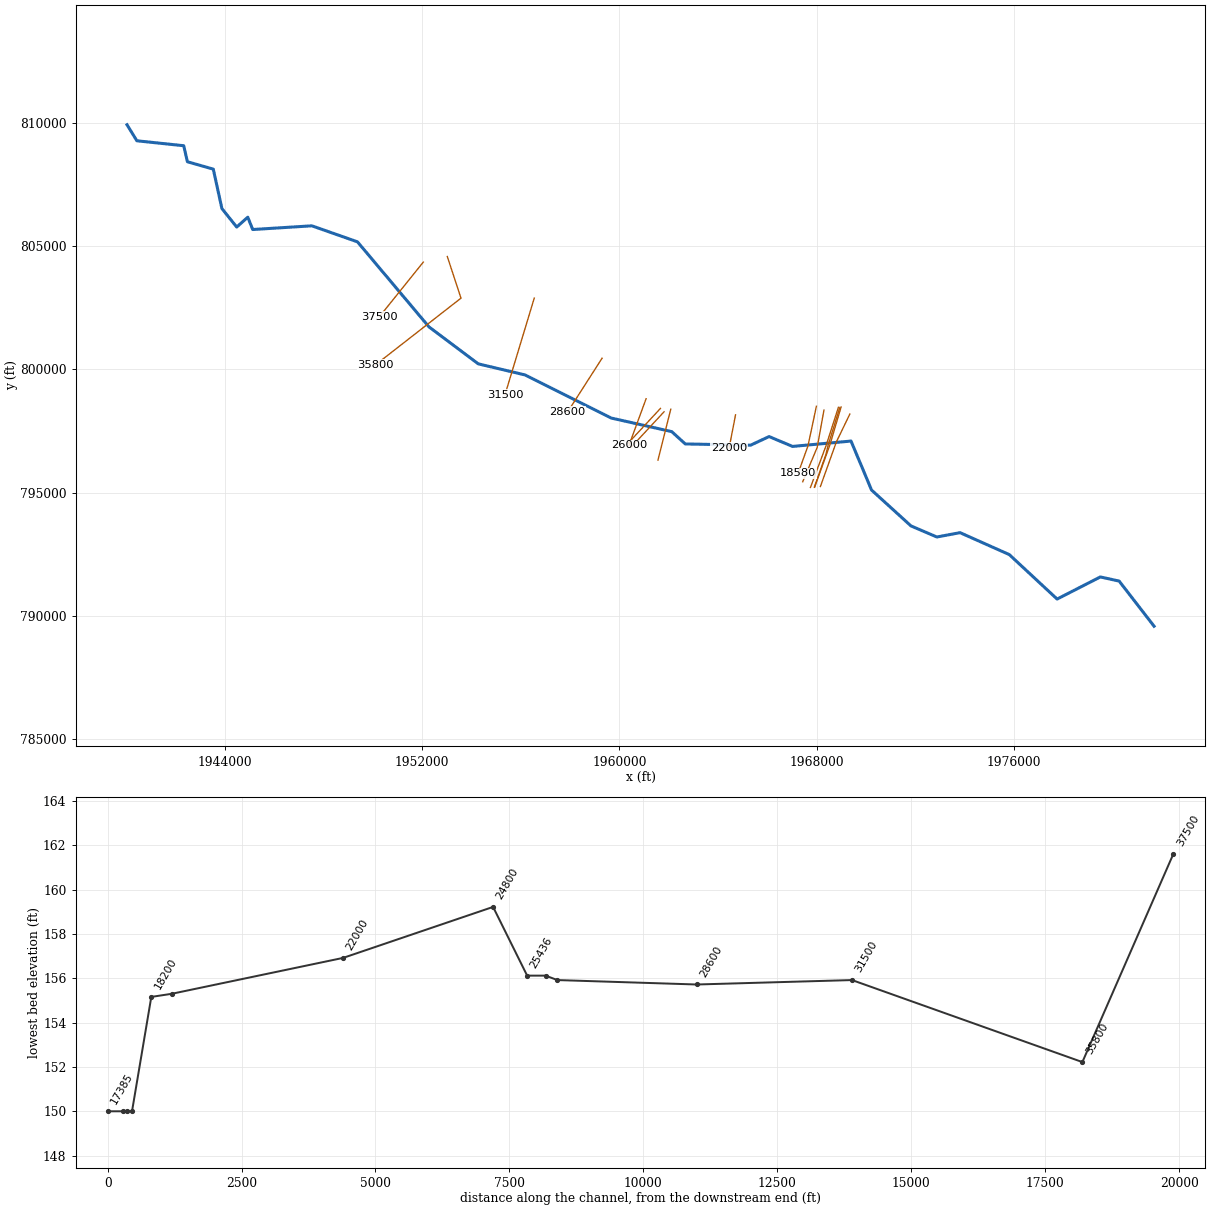
--- CCR_Prelim_Updated.prj (project) ---

Proj Title=CCR SALUDA RIVER Detailed Study
Current Plan=p07
Default Exp/Contr=0.3,0.1
English Units
Geom File=g01
Geom File=g02
Geom File=g03
Flow File=f01
Flow File=f02
Flow File=f03
Plan File=p01
Plan File=p02
Plan File=p03
Plan File=p04
Plan File=p05
Plan File=p06
Plan File=p07
Plan File=p08
Y Axis Title=Elevation
X Axis Title(PF)=Main Channel Distance
X Axis Title(XS)=Station
BEGIN DESCRIPTION:
SALUDA RIVER
END DESCRIPTION:
DSS Export Rating Curves= 0
DSS Export Rating Curve Sorted= 0
DSS Export Volume Flow Curves= 0
DXF Filename=..\Preliminary Model 2-2018\SALUDA RIVER\SALUDA RIVER\Simulations\SaludaRiver\SALUDA RIVER.
DXF OffsetX= 0
DXF OffsetY= 0
DXF ScaleX= 1
DXF ScaleY= 10

--- CCR_Prelim_Updated.p07 (plan) ---

Plan Title=Combined Model with Bridge
Program Version=5.03
Short Identifier=ComboBridge
Geom File=g03
Flow File=f03
Subcritical Flow
K Sum by GR= 0
Std Step Tol= 0.01
Critical Tol= 0.01
Num of Std Step Trials= 20
Max Error Tol= 0.3
Flow Tol Ratio= 0.001
Split Flow NTrial= 30
Split Flow Tol= 0.02
Split Flow Ratio= 0.02
Log Output Level= 0
Friction Slope Method= 1
Unsteady Friction Slope Method= 2
Unsteady Bridges Friction Slope Method= 1
Parabolic Critical Depth
Global Vel Dist= 1 , 1 , 1
Global Log Level= 0
CheckData=True
Encroach Param=-1 ,0,0, 0
BEGIN DESCRIPTION:
This is the Richland County Prelminary model combined with the HEC-2 Effective model for Lexington County with updated I-26 and I-20 Bridges from mapping.
END DESCRIPTION:
Computation Interval=1MIN
Output Interval=1HOUR
Instantaneous Interval=1HOUR
Mapping Interval=1HOUR
Run HTab= 0
Run UNet= 0
Run Sediment= 0
Run PostProcess= 0
Run WQNet= 0
Run RASMapper= 0
UNET Theta= 1
UNET Theta Warmup= 1
UNET ZTol= 0.02
UNET ZSATol= 0.02
UNET MxIter= 20
UNET Max Iter WO Improvement= 0
UNET MaxInSteps= 0
UNET DtIC= 0
UNET DtMin= 0
UNET MaxCRTS= 20
UNET WFStab= 2
UNET SFStab= 1
UNET WFX= 1
UNET SFX= 1
UNET DSS MLevel= 4
UNET Pardiso=0
UNET DZMax Abort= 100
UNET Use Existing IB Tables=-1
UNET Froude Reduction=False
UNET Froude Limit= 0.8
UNET Froude Power= 4
UNET Time Slicing=0,0, 5
UNET D1 Cores= 0
UNET D2 Coriolis=0
UNET D2 Cores= 0
UNET D2 Theta= 1
UNET D2 Theta Warmup= 1
UNET D2 Z Tol= 0.01
UNET D2 Volume Tol= 0.01
UNET D2 Max Iterations= 20
UNET D2 Equation= 0
UNET D2 RampUpFraction=0.1
UNET D2 TimeSlices= 1
UNET D2 BCVolumeCheck=0
UNET D1D2 MaxIter= 0
UNET D1D2 ZTol=0.01
UNET D1D2 QTol=0.1
UNET D1D2 MinQTol=1
Write IC File= 0
Write IC File at Fixed DateTime=0
Write IC File at Sim End=0
Echo Input=False
Echo Parameters=False
Echo Output=False
Write Detailed= 0
HDF Write Warmup=0
HDF Write Time Slices=0
HDF Flush=0
HDF Face Node Velocities=0
HDF Compression= 1
HDF Chunk Size= 1
HDF Spatial Parts= 1
HDF Use Max Rows=0
HDF Fixed Rows= 1
Calibration Method= 0
Calibration Iterations= 20
Calibration Max Change=0.05
Calibration Tolerance=0.2
Calibration Maximum=1.5
Calibration Minimum=0.5
Calibration Optimization Method= 1
WQ AD Non Conservative
WQ ULTIMATE=-1
WQ Max Comp Step=1HOUR
WQ Output Interval=15MIN
WQ Output Selected Increments= 0
WQ Output face flow=0
WQ Output face velocity=0
WQ Output face area=0
WQ Output face dispersion=0
WQ Output cell volume=0
WQ Output cell surface area=0
WQ Output cell continuity=0
WQ Output cumulative cell continuity=0
WQ Output face conc=0
WQ Output face dconc_dx=0
WQ Output face courant=0
WQ Output face peclet=0
WQ Output face adv mass=0
WQ Output face disp mass=0
WQ Output cell mass=0
WQ Output cell source sink temp=0
WQ Output nsm pathways=0
WQ Output nsm derived pathways=0
WQ Output MaxMinRange=-1
WQ Daily Max Min Mean=-1
WQ Daily Range=0
WQ Daily Time=0
WQ Create Restart=0
WQ Fixed Restart=0
WQ System Summary=0
WQ Write To DSS=0
WQ Use Fixed Temperature=0
Sorting and Armoring Iterations= 10
XS Update Threshold= 0.02
Bed Roughness Predictor= 0
Hydraulics Update Threshold= 0.02
Energy Slope Method= 1
Volume Change Method= 1
Sediment Retention Method= 0
XS Weighting Method= 0
Number of US Weighted Cross Sections= 1
Number of DS Weighted Cross Sections= 1
Upstream XS Weight=0
Main XS Weight=1
Downstream XS Weight=0
Number of DS XS's Weighted with US Boundary= 1
Upstream Boundary Weight= 1
Weight of XSs Associated with US Boundary= 0
Number of US XS's Weighted with DS Boundary= 1
Downstream Boundary Weight= 0.5
Weight of XSs Associated with DS Boundary= 0.5
Percentile Method= 0
Sediment Output Level= 4
Mass or Volume Output= 0
Output Increment Type= 1
Profile and TS Output Increment= 1
XS Output Flag= 0
XS Output Increment= 10
Write Gradation File= 0
Read Gradation Hotstart= 0
Write HDF5 File= 1
Write DSS Sediment File= 0
SV Curve= 0
Specific Gage Flag= 0

--- CCR_Prelim_Updated.p01 (plan) ---

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Plan Title=Multiple Run
Short Identifier=Multiple
Geom File=g01
Flow File=f01
Global Vel Dist=  1 , 1 , 1
Encroach Param= -1, 0, 0, 0
Multiple Run

--- CCR_Prelim_Updated.p02 (plan) ---

Plan Title=Floodway Run
Short Identifier=Floodway
Geom File=g01
Flow File=f02
Subcritical Flow
K Sum by GR= 0
Std Step Tol= 0.01
Critical Tol= 0.01
Num of Std Step Trials= 20
Max Error Tol= 0.3
Flow Tol Ratio= 0.001
Split Flow NTrial= 30
Split Flow Tol= 0.02
Split Flow Ratio= 0.02
Log Output Level= 0
Friction Slope Method= 1
Unsteady Friction Slope Method= 2
Unsteady Bridges Friction Slope Method= 1
Parabolic Critical Depth
Global Vel Dist=  1 , 1 , 1
Global Log Level= 0
CheckData=True
Encroach Param=-1,0,0,2
Encroach River=SALUDA RIVER
Encroach Reach=Reach-1
Encroach Node=18580
       1    3965    5393
Encroach Node=18200
       1    4500    5425
Encroach Node=17840
       1    4800    5200
Encroach Node=17790
       1    4800    5200
Encroach Node=17750
       1    4800    5200
Encroach Node=17665
       1    4660    5290
Encroach Node=17540
       1    4660    5290
Encroach Node=17385
       1    4635    5285
Encroach Node=17000
       1    4700    5300
Encroach Node=16600
       1    4700    5300
Encroach Node=16200
       1    4640    5350
Encroach Node=15700
       1    4700    5500
Encroach Node=15200
       1    4640    5560
Encroach Node=14700
       1    4735    5598
Encroach Node=14200
       1    4800    5540
Encroach Node=13600
       1    4800    5500
Encroach Node=13000
       1    4821    5340
Encroach Node=12500
       1    4821    5382
Encroach Node=12000
       1    4842    5120
Encroach Node=11500
       1    4839    5215
Encroach Node=11000
       1    4834    5179
Encroach Node=10500
       1    4801    5195
Encroach Node=10000
       1    4820    5205
Encroach Node=9500
       1    4810    5220
Encroach Node=9000
       1    4817    5200
Encroach Node=8500
       1    4728    5285
Encroach Node=8240
       1    4640    5465
Encroach Node=7900
       1    4720    5565
Encroach Node=7400
       1    4728    5253
Encroach Node=6900
       1    4762    5167
Encroach Node=6450
       1    4730    5193
Encroach Node=6350
       1    4730    5193
Encroach Node=6270
       1    4719    5204
Encroach Node=5900
       1    4830    5165
Encroach Node=5400
       1    4795    5150
Encroach Node=4900
       1    4830    5150
Encroach Node=4400
       1    4880    5150
Encroach Node=3900
       1    4860    5150
Encroach Node=3400
       1    4844    5150
Encroach Node=2900
       1    4700    5275
Encroach Node=2400
       1    4550    5675
Encroach Node=2000
       1    4750    5700
Encroach Node=1600
       1    4750    5600
Encroach Node=1100
       1    4750    5350
BEGIN DESCRIPTION:
Floodway Run
END DESCRIPTION:

--- CCR_Prelim_Updated.p03 (plan) ---

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Plan Title=Plan 03
Short Identifier=Plan 03
Geom File=g02
Flow File=f01
Multiple Run

--- CCR_Prelim_Updated.p04 (plan) ---

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Plan Title=Plan 04
Short Identifier=Plan 04
Geom File=g02
Flow File=f01
Multiple Run

--- CCR_Prelim_Updated.p05 (plan) ---

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Plan Title=Combined Model
Short Identifier=Combo
Geom File=g02
Flow File=f01
This is the Richland County Prelminary model combined with the HEC-2 Effective model for Lexington County

--- CCR_Prelim_Updated.p06 (plan) ---

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Plan Title=Plan 06
Short Identifier=Combo
Geom File=g02
Flow File=f01
This is the Richland County Prelminary model combined with the HEC-2 Effective model for Lexington County

--- CCR_Prelim_Updated.p08 (plan) ---

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Plan Title=Plan 08
Short Identifier=Plan 08
Geom File=g03
Flow File=f01

--- CCR_Prelim_Updated.f03 (steady flow) ---

Flow Title=Multiple_Full Model
Program Version=5.03
Number of Profiles= 5
Profile Names=10-year,25-year,50-year,100-year,500-year
River Rch & RM=SALUDA RIVER,Reach-1         ,37500
   29600   39400   48300   71000   89900
River Rch & RM=SALUDA RIVER,Reach-1         ,18580
   29600   39400   48300   58600   89900
River Rch & RM=SALUDA RIVER,Reach-1         ,17665
   29600   39400   48300   58600   89900
Boundary for River Rch & Prof#=SALUDA RIVER,Reach-1         , 1
Up Type= 0
Dn Type= 3
Dn Slope=0.00105
Boundary for River Rch & Prof#=SALUDA RIVER,Reach-1         , 2
Up Type= 0
Dn Type= 3
Dn Slope=0.00105
Boundary for River Rch & Prof#=SALUDA RIVER,Reach-1         , 3
Up Type= 0
Dn Type= 3
Dn Slope=0.00105
Boundary for River Rch & Prof#=SALUDA RIVER,Reach-1         , 4
Up Type= 0
Dn Type= 3
Dn Slope=0.00105
Boundary for River Rch & Prof#=SALUDA RIVER,Reach-1         , 5
Up Type= 0
Dn Type= 3
Dn Slope=0.00105
DSS Import GetInterval= 0
DSS Import GetPeak= 0
DSS Import FillOption= 0

--- CCR_Prelim_Updated.f01 (steady flow) ---

Flow Title=Multiple
Program Version=5.03
Number of Profiles= 5
Profile Names=10-year,25-year,50-year,100-year,500-year
River Rch & RM=SALUDA RIVER,Reach-1         ,18580
   29600   39400   48300   58600   89900
River Rch & RM=SALUDA RIVER,Reach-1         ,17665
   29600   39400   48300   58600   89900
Boundary for River Rch & Prof#=SALUDA RIVER,Reach-1         , 1
Up Type= 0
Dn Type= 3
Dn Slope=0.00105
Boundary for River Rch & Prof#=SALUDA RIVER,Reach-1         , 2
Up Type= 0
Dn Type= 3
Dn Slope=0.00105
Boundary for River Rch & Prof#=SALUDA RIVER,Reach-1         , 3
Up Type= 0
Dn Type= 3
Dn Slope=0.00105
Boundary for River Rch & Prof#=SALUDA RIVER,Reach-1         , 4
Up Type= 0
Dn Type= 3
Dn Slope=0.00105
Boundary for River Rch & Prof#=SALUDA RIVER,Reach-1         , 5
Up Type= 0
Dn Type= 3
Dn Slope=0.00105
DSS Import GetInterval= 0
DSS Import GetPeak= 0
DSS Import FillOption= 0

--- CCR_Prelim_Updated.f02 (steady flow) ---

Flow Title=Floodway
Number of Profiles=2
Profile Names=100-year,100-FW
River Rch & RM= SALUDA RIVER,Reach-1,18580
   58600   58600
River Rch & RM= SALUDA RIVER,Reach-1,17665
   58600   58600
Boundary for River Rch & Prof#=SALUDA RIVER,Reach-1,1
Up Type=0
Dn Type=3
Dn Slope=0.00105
Boundary for River Rch & Prof#=SALUDA RIVER,Reach-1,2
Up Type=0
Dn Type=3
Dn Slope=0.00105

--- CCR_Prelim_Updated.g03 (geometry) ---

Geom Title=Ex_con_updated bridge
Program Version=5.03

River Reach=SALUDA RIVER    ,Reach-1
Reach XY= 30
        1940025.         809925.        1940425.         809275.
        1942325.         809075.        1942475.         808425.
        1943525.         808125.        1943875.         806525.
        1944475.         805775.        1944925.         806175.
        1945125.         805675.        1947525.         805825.
        1949375.         805175.        1952275.         801725.
        1954275.         800225.        1956175.         799775.
        1959675.         798025.        1962125.         797475.
        1962675.         796975.        1965325.         796925.
        1966075.         797275.        1967025.         796875.
        1969399.        797092.6      1970231.69       795104.72
      1971830.25       793650.36      1972881.79       793200.27
      1973823.05        793375.8      1975820.27       792485.86
      1977760.18       790682.11      1979514.91       791579.55
      1980277.87       791410.79      1981693.76        789580.3

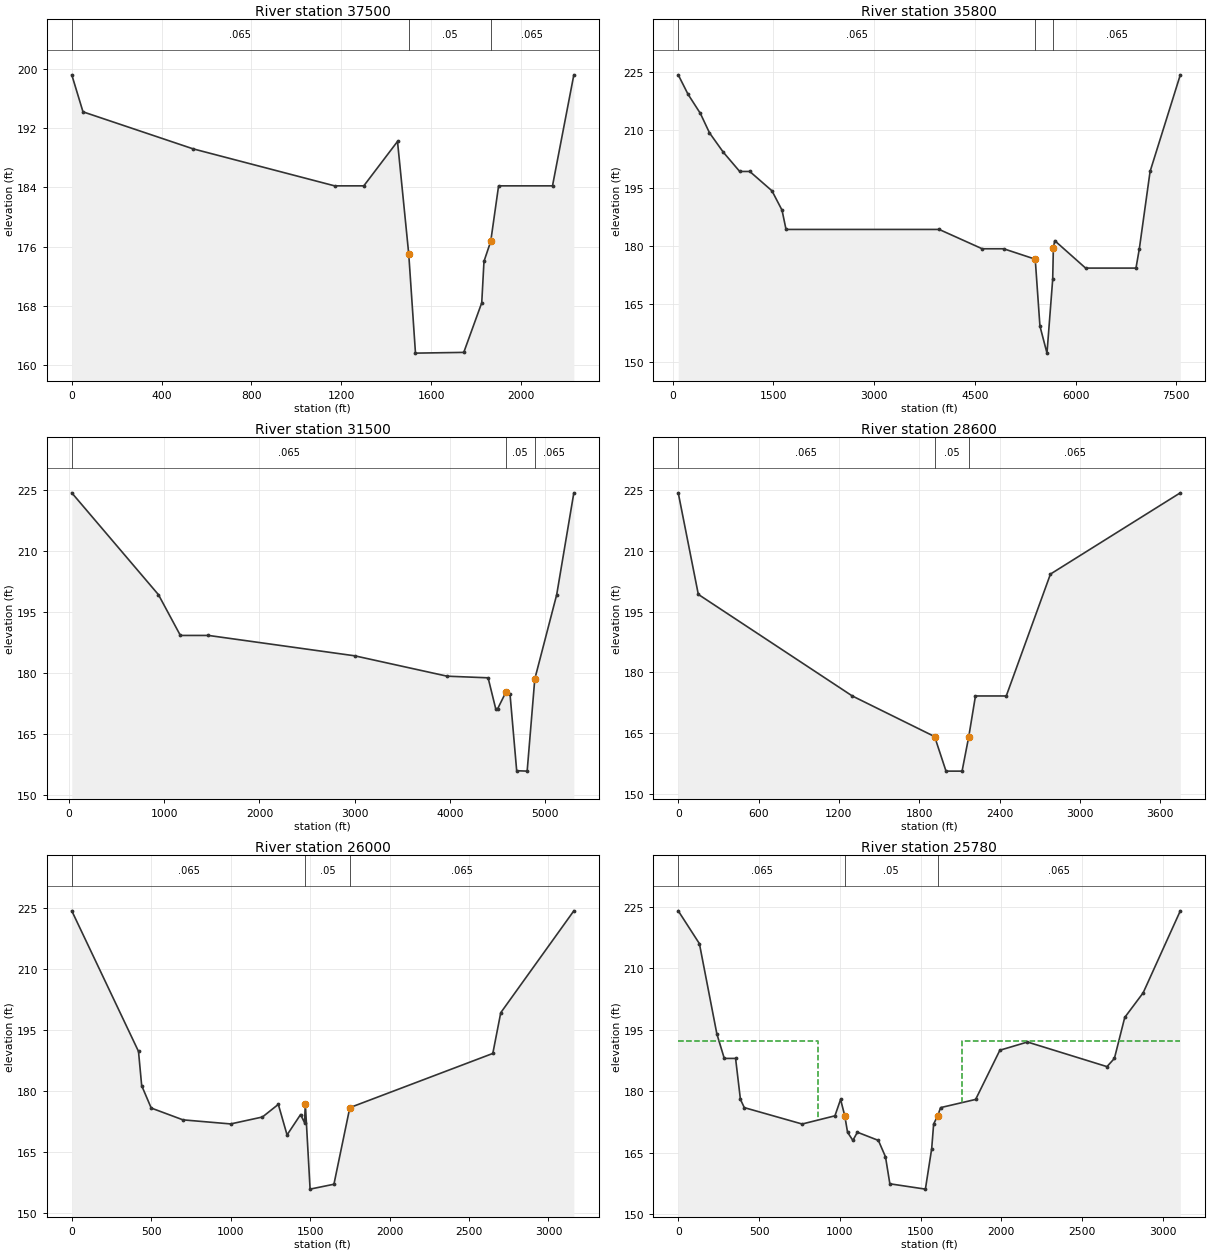
Type RM Length L Ch R = 1 ,37500   ,1700,1700,1700
BEGIN DESCRIPTION:
FEMA XS: O
END DESCRIPTION:
XS GIS Cut Line= 2
     1952046.143      804353.213     1950260.573      802133.301
#Sta/Elev= 15
       0  199.22      50  194.22     540  189.22    1170  184.22    1300  184.22
    1450  190.22    1500  175.02    1530  161.62    1745  161.72    1825  168.42
    1835  174.02    1865  176.72    1900  184.22    2140  184.22    2235  199.22
#Mann= 3 , 0 , 0
       0    .065       0    1500     .05       0    1865    .065       0
Bank Sta=1500,1865
XS Rating Curve= 0 ,0
Exp/Cntr=0.3,0.1

Type RM Length L Ch R = 1 ,35800   ,4100,4300,4400
BEGIN DESCRIPTION:
FEMA XS: N
END DESCRIPTION:
XS GIS Cut Line= 3
     1953019.318      804580.042     1953574.619      802890.459
     1950104.282      800182.426
#Sta/Elev= 24
      85  224.22     230  219.22     415  214.22     550  209.22     755  204.22
    1000  199.22    1150  199.22    1480  194.22    1630  189.22    1690  184.22
    3970  184.22    4610  179.22    4930  179.22    5400  176.52    5470  159.22
    5575  152.22    5660  171.32    5670  179.42    5690  181.32    6150  174.22
    6900  174.22    6950  179.22    7110  199.22    7560  224.22
#Mann= 3 , 0 , 0
      85    .065       0    5400     .05       0    5670    .065       0
Bank Sta=5400,5670
XS Rating Curve= 0 ,0
Exp/Cntr=0.3,0.1

Type RM Length L Ch R = 1 ,31500   ,2900,2900,2900
BEGIN DESCRIPTION:
FEMA XS: M
END DESCRIPTION:
XS GIS Cut Line= 2
     1956547.939      802894.387     1955359.257      798968.257
#Sta/Elev= 16
      30  224.22     940  199.22    1170  189.22    1465  189.22    3000  184.22
    3970  179.22    4400  178.82    4480  171.22    4500  171.22    4585  175.22
    4630  174.82    4700  156.02    4810  155.92    4890  178.52    5120  199.22
    5300  224.22
#Mann= 3 , 0 , 0
      30    .065       0    4585     .05       0    4890    .065       0
Bank Sta=4585,4890
XS Rating Curve= 0 ,0
Exp/Cntr=0.3,0.1

Type RM Length L Ch R = 1 ,28600   ,2600,2600,2600
BEGIN DESCRIPTION:
FEMA XS: L
END DESCRIPTION:
XS GIS Cut Line= 2
     1959299.258      800453.524     1957901.124      798273.368
#Sta/Elev= 11
       0  224.22     150  199.22    1300  174.22    1915  164.22    2000  155.72
    2120  155.72    2170  164.22    2220  174.22    2450  174.22    2780  204.22
    3750  224.22
#Mann= 3 , 0 , 0
       0    .065       0    1915     .05       0    2170    .065       0
Bank Sta=1915,2170
XS Rating Curve= 0 ,0
Exp/Cntr=0.3,0.1

Type RM Length L Ch R = 1 ,26000   ,320,220,170
BEGIN DESCRIPTION:
FEMA XS: K
END DESCRIPTION:
XS GIS Cut Line= 2
     1961084.429      798807.229     1960388.625      796915.593
#Sta/Elev= 18
       0  224.22     420  189.72     440  181.32     500  175.82     700  172.92
    1000  171.92    1200  173.62    1300  176.72    1355  169.22    1440  174.22
    1465  172.22    1470  176.82    1500  155.92    1650  157.12    1750  175.92
    2650  189.22    2700  199.22    3160  224.22
#Mann= 3 , 0 , 0
       0    .065       0    1470     .05       0    1750    .065       0
Bank Sta=1470,1750
XS Rating Curve= 0 ,0
Exp/Cntr=0.5,0.3

Type RM Length L Ch R = 1 ,25780   ,344,344,344
BEGIN DESCRIPTION:
New Section US I-20
END DESCRIPTION:
XS GIS Cut Line= 2
     1961666.693      798416.499     1960345.534      796994.429
#Sta/Elev= 30
       0     224     131     216     239     194     285     188     355     188
     385     178     409     176     767     172     970     174    1005     178
    1031     174    1048     170    1081     168    1109     170    1239     168
    1283     164    1310  157.42    1530  156.12    1569     166    1581     172
    1606     174    1624     176    1841     178    1991     190    2162     192
    2654     186    2700     188    2764     198    2878     204    3108     224
#Mann= 3 , 0 , 0
       0    .065       0    1031     .05       0    1606    .065       0
#XS Ineff= 2 , 0
       0   866.1  192.37  1753.8       0  192.37
Permanent Ineff=
       F       F
Bank Sta=1031,1606
XS Rating Curve= 0 ,0
Exp/Cntr=0.5,0.3

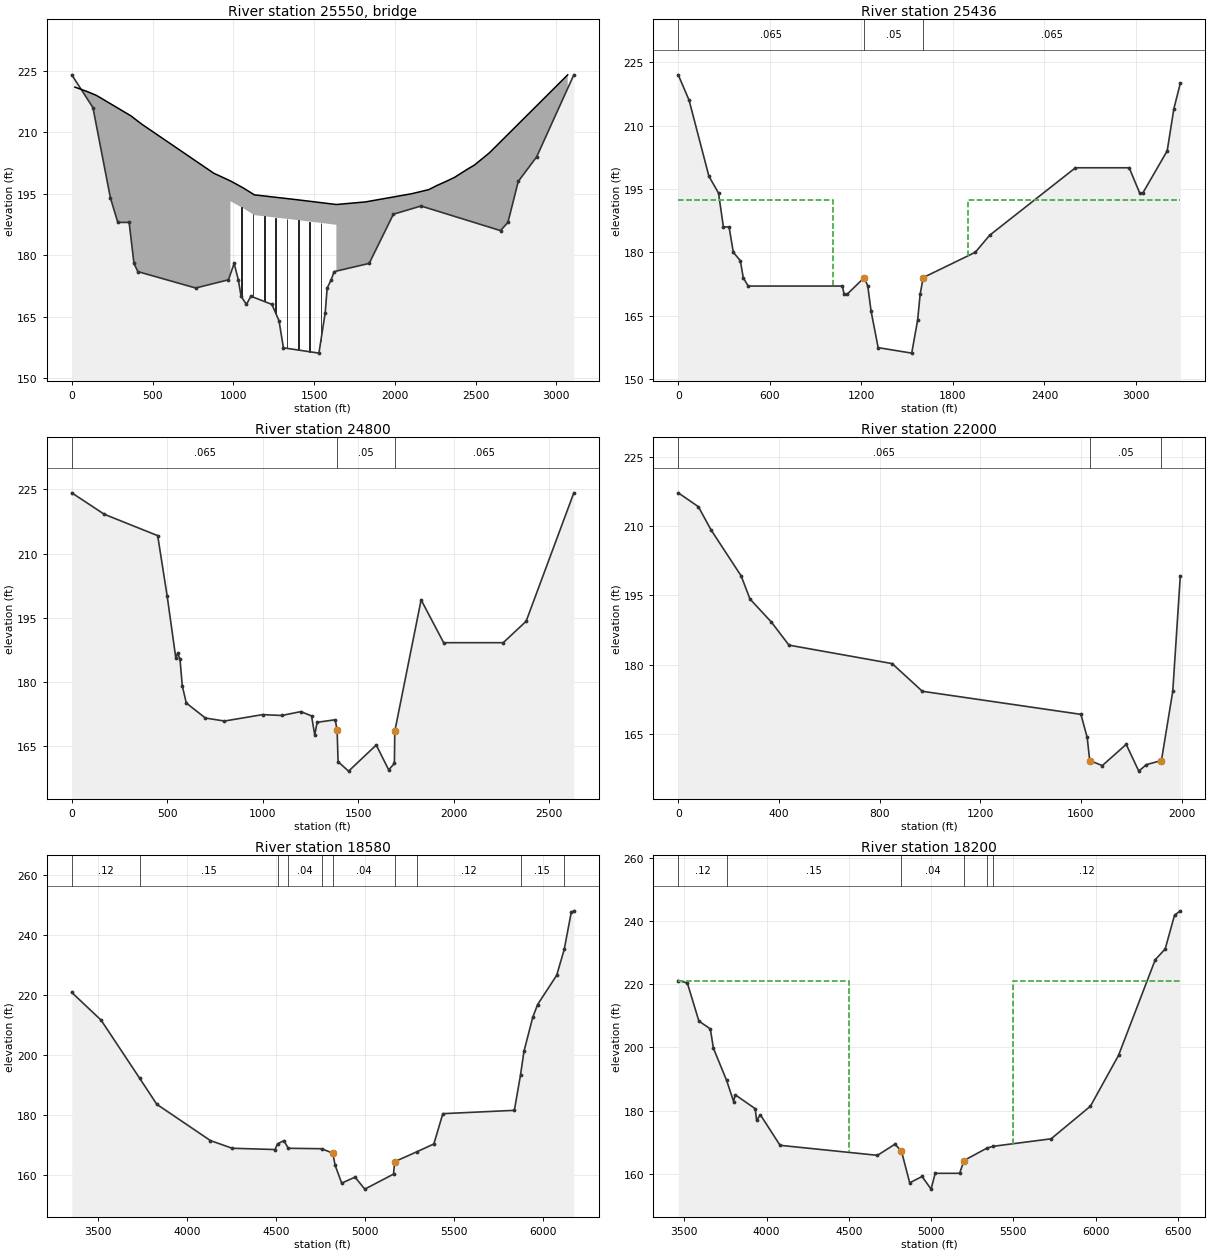
Type RM Length L Ch R = 3 ,25550   ,,,
Bridge Culvert--1,0,-1,-1, 0
Deck Dist Width WeirC Skew NumUp NumDn MinLoCord MaxHiCord MaxSubmerge Is_Ogee
95,108,2.5,0, 25, 26, 191.32, , 0.98, 0, 5.8,5.8,,
    19.5    90.2     152     366     399     432     879     982     982    1061
    1130    1391    1638    1638  1817.7    2104    2210    2260    2317    2370
    2410    2450    2493    2586    3070
     221     220     219     214     213     212     200 198.123 198.123 196.426
  194.73  193.55  192.37  192.37     193     195     196     197     198     199
     200     201     202     205     224
                                                                 193.173 191.476
  189.78   188.6  187.42
                                        
       0   167.5   238.2     300     514     547     580    1027    1130    1130
    1209    1278    1539    1786    1786  1965.7    2252    2358    2408    2465
    2518    2558    2598    2641    2734    3218
     222     221     220     219     214     213     212     200 198.123 198.123
 196.426  194.73  193.55  192.37  192.37     193     195     196     197     198
     199     200     201     202     205     224
                                                                         193.173
 191.476  189.78   188.6  187.42
                                                
Pier Skew, UpSta & Num, DnSta & Num=  ,1052, 2 ,1200, 2 , 0 , 0 , 0 ,,
     3.5     3.5
   156.9   192.2
     3.5     3.5
   156.9   192.2
Pier Skew, UpSta & Num, DnSta & Num=  ,1122, 2 ,1270, 2 , 0 , 0 , 0 ,,
     3.5     3.5
   156.9   192.2
     3.5     3.5
   156.9   192.2
Pier Skew, UpSta & Num, DnSta & Num=  ,1192, 2 ,1340, 2 , 0 , 0 , 0 ,,
     3.5     3.5
   156.9   192.2
     3.5     3.5
   156.9   192.2
Pier Skew, UpSta & Num, DnSta & Num=  ,1262, 2 ,1410, 2 , 0 , 0 , 0 ,,
     3.5     3.5
   156.9 193.173
     3.5     3.5
   156.9   192.2
Pier Skew, UpSta & Num, DnSta & Num=  ,1332, 2 ,1480, 2 , 0 , 0 , 0 ,,
     3.5     3.5
   156.9   192.2
     3.5     3.5
   156.9   192.2
Pier Skew, UpSta & Num, DnSta & Num=  ,1402, 2 ,1550, 2 , 0 , 0 , 0 ,,
     3.5     3.5
   156.9   192.2
     3.5     3.5
   156.9   192.2
Pier Skew, UpSta & Num, DnSta & Num=  ,1472, 2 ,1620, 2 , 0 , 0 , 0 ,,
     3.5     3.5
   156.9   192.2
     3.5     3.5
   156.9   192.2
Pier Skew, UpSta & Num, DnSta & Num=  ,1542, 2 ,1690, 2 , 0 , 0 , 0 ,,
     3.5     3.5
   156.9   192.2
     3.5     3.5
   156.9   192.2
Abutment Skew #Up #Dn= , 3 , 3
     982     986    1020
 191.173 191.173 174.173
    1130    1134    1168
 191.173 191.173 174.173
Abutment Skew #Up #Dn= , 3 , 3
    1542    1634    1638
  139.42  185.42  185.42
    1692    1784    1786
  139.42  185.42  185.42
BR Coef= 0 , 0 , 1 ,1.25, 0 ,,,1.3,0,,2,191.42
WSPro=,,,, 1 ,,,, 0 ,,,, 0 ,,,,-1 ,-1 ,-1 , 0 , 0 , 0 , 0 , 0
BC Design=,, 0 ,, 0 ,,,,,,
BC Use User HTab Curves=0
BC User HTab FreeFlow(D)= 0

Type RM Length L Ch R = 1 ,25436   ,636,636,636
BEGIN DESCRIPTION:
New Section DS of I-20
END DESCRIPTION:
XS GIS Cut Line= 2
     1961813.217      798280.372     1960492.059      796858.302
#Sta/Elev= 30
       0     222      71     216     201     198     264     194     296     186
     333     186     361     180     407     178     426     174     458     172
    1076     172    1087     170    1105     170    1219     174    1242     172
    1264     166    1310  157.42    1530  156.12    1569     164    1585     170
    1605     174    1947     180    2040     184    2603     200    2955     200
    3024     194    3044     194    3204     204    3248     214    3290     220
#Mann= 3 , 0 , 0
       0    .065       0    1219     .05       0    1605    .065       0
#XS Ineff= 2 , 0
       0  1014.1  192.37  1901.8       0  192.37
Permanent Ineff=
       F       F
Bank Sta=1219,1605
XS Rating Curve= 0 ,0
Exp/Cntr=0.5,0.3

Type RM Length L Ch R = 1 ,24800   ,2800,2800,2800
BEGIN DESCRIPTION:
FEMA XS: J
END DESCRIPTION:
XS GIS Cut Line= 2
     1962086.565       798384.88     1961565.785      796319.252
#Sta/Elev= 30
       0  224.22     170  219.22     450  214.22     500  200.02     545  185.62
     555  186.82     567  185.32     579  179.12     600  175.12     700  171.62
     800  170.92    1000  172.42    1100  172.22    1200  173.12    1256  172.12
    1273  167.62    1285  170.62    1380  171.22    1390  168.72    1395  161.42
    1450  159.22    1595  165.32    1660  159.52    1690  161.02    1692  168.52
    1830  199.22    1948  189.22    2260  189.22    2380  194.22    2630  224.22
#Mann= 3 , 0 , 0
       0    .065       0    1390     .05       0    1692    .065       0
Bank Sta=1390,1692
XS Rating Curve= 0 ,0
Exp/Cntr=0.5,0.3

Type RM Length L Ch R = 1 ,22000   ,3200,3200,3200
BEGIN DESCRIPTION:
FEMA XS: I
END DESCRIPTION:
XS GIS Cut Line= 2
     1964713.343      798155.587     1964453.567      796811.327
#Sta/Elev= 19
       0  217.22      80  214.22     130  209.22     250  199.22     285  194.22
     370  189.22     440  184.22     850  180.22     970  174.22    1600  169.22
    1625  164.22    1635  159.22    1685  158.12    1780  162.72    1830  156.92
    1860  158.32    1920  159.22    1965  174.22    1995  199.22
#Mann= 3 , 0 , 0
       0    .065       0    1635     .05       0    1920    .065       0
Bank Sta=1635,1920
XS Rating Curve= 0 ,0
Exp/Cntr=0.3,0.1

Type RM Length L Ch R = 1 ,18580   ,369,380,360
BEGIN DESCRIPTION:
SALUDA RIVER 45.0
END DESCRIPTION:
XS GIS Cut Line= 3
      1967994.19       798504.51        1967652.       796893.35
      1967253.26       795788.08
#Sta/Elev= 30
  3352.9  220.87  3517.8  211.64  3733.9  192.32  3830.8  183.59  4132.3  171.49
  4254.4  168.93  4495.5   168.5  4509.4  170.37  4545.2  171.47    4570  168.92
  4757.1  168.77    4820   167.3    4833   163.3    4870   157.3    4945   159.3
    5000   155.3  5161.3   160.3  5168.1  164.46  5295.1  167.82  5388.1  170.36
  5438.6  180.46  5840.6  181.57  5875.2  193.34  5894.7  201.26  5943.8  212.54
  5971.3  216.85  6078.6   226.6  6120.9  235.23  6160.4  247.58    6175  248.09
#Mann= 10 ,-1 , 0
  3352.9     .12       0  3733.9     .15       0  4509.4     .08       0
    4570     .04       0  4757.1     .15       0    4820     .04       0
  5168.1     .15       0  5295.1     .12       0  5875.2     .15       0
  6120.9     .12       0
Bank Sta=4820,5168.1
XS Rating Curve= 0 ,0
Exp/Cntr=0.3,0.1

Type RM Length L Ch R = 1 ,18200   ,399,360,425
BEGIN DESCRIPTION:
SALUDA RIVER 44.0
END DESCRIPTION:
XS GIS Cut Line= 3
      1968300.98       798348.76      1968027.38       796836.81
      1967440.11       795441.03
#Sta/Elev= 30
  3463.5   221.2  3518.9  220.41    3589  208.36  3658.5  205.88  3677.1   199.8
    3757  189.63  3800.2  182.87  3809.3  185.04  3931.2  180.63  3939.6  176.98
  3962.8  178.68  4082.2  169.03  4674.2  165.86  4780.6  169.39    4820  167.16
    4870  157.16    4945  159.16    5000  155.16  5024.7  160.16  5173.5  160.17
  5199.8  164.22  5340.1  168.17  5377.5  168.72  5729.2  171.09  5968.2  181.42
  6138.8   197.5  6361.9  227.77  6422.4   231.2    6479  241.85  6514.3  243.26
#Mann= 6 ,-1 , 0
  3463.5     .12       0    3757     .15       0    4820     .04       0
  5199.8     .15       0  5340.1     .04       0  5377.5     .12       0
#XS Ineff= 2 , 0
       0    4500     221    5500       0     221
Permanent Ineff=
       F       F
Bank Sta=4820,5199.8
XS Rating Curve= 0 ,0
Exp/Cntr=0.5,0.3

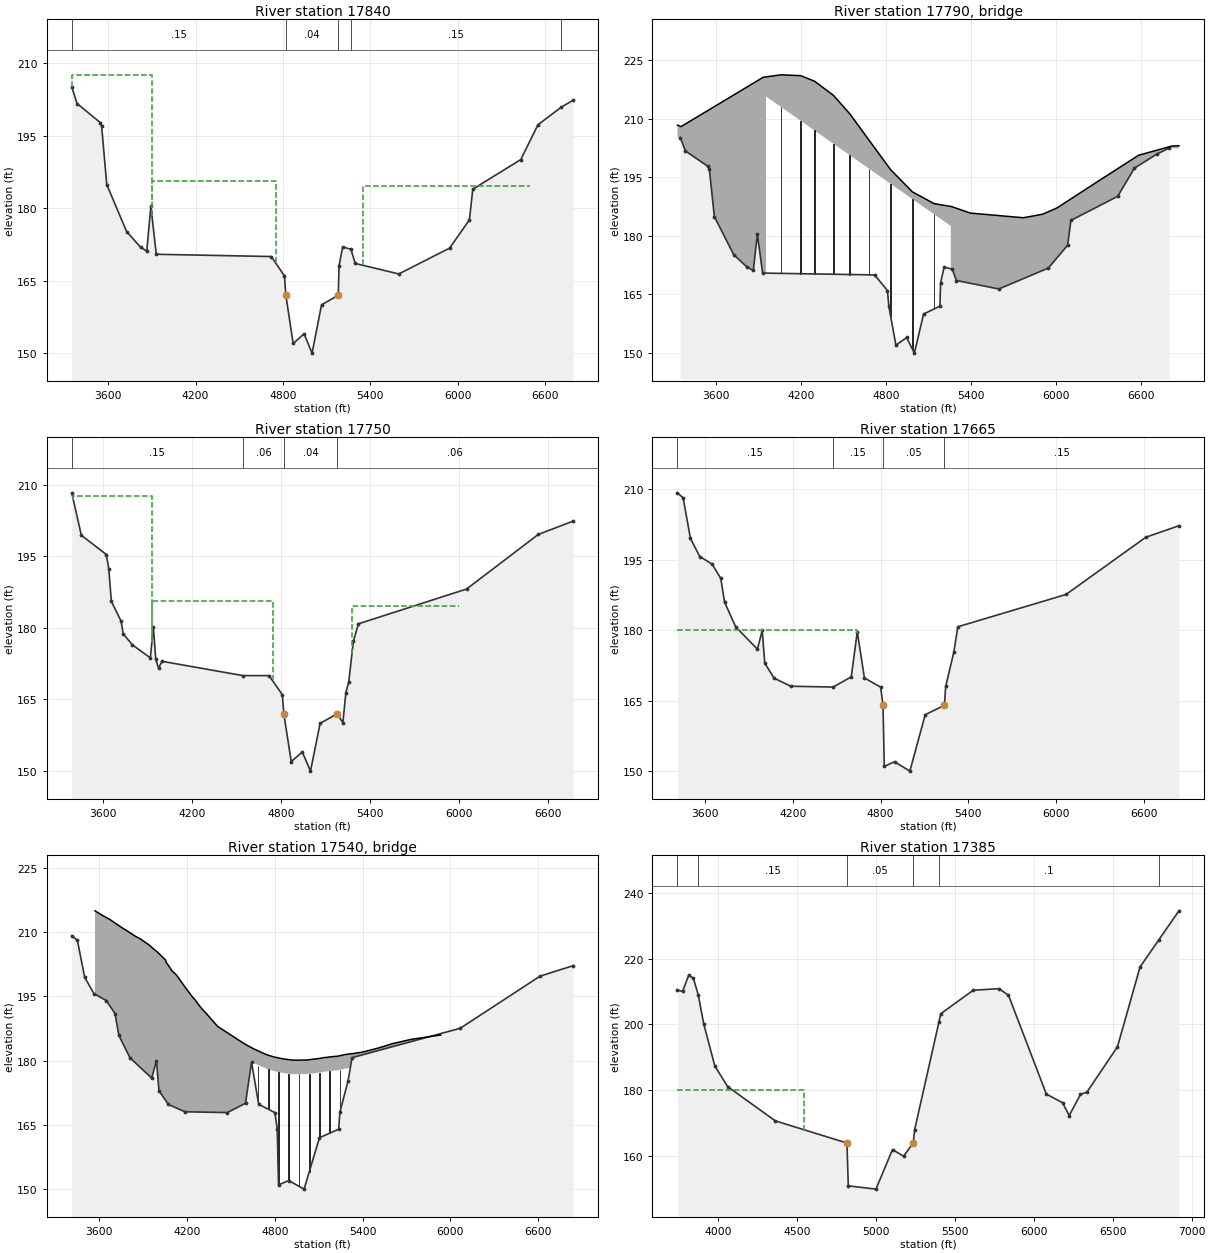
Type RM Length L Ch R = 1 ,17840   ,77,90,170
BEGIN DESCRIPTION:
SALUDA RIVER (I-26 Ramp - US)
END DESCRIPTION:
XS GIS Cut Line= 3
       1968887.4       798461.11      1968380.66       796890.12
      1967753.47       795210.18
#Sta/Elev= 30
  3349.3  205.13  3386.2  201.67  3545.5  197.74  3554.5  197.01  3589.8  184.91
  3726.1  175.18  3822.5  171.92  3864.5  171.14  3892.9   180.4    3930  170.47
    4720     170    4810     166    4820     162    4870     152    4945     154
    5000     150    5065     160    5180     162    5185     168    5210     172
  5267.1  171.49  5296.2  168.57  5595.7   166.4  5944.6  171.75  6080.7  177.59
  6103.7  183.94  6433.2  190.08  6551.5  197.29  6712.6  200.96  6793.2  202.38
#Mann= 5 ,-1 , 0
  3349.3     .15       0    4820     .04       0    5180     .04       0
  5267.1     .15       0  6712.6     .11       0
#XS Ineff= 3 ,-1
    3300    3900  207.63  3900.1    4750   185.7    5350    6500  184.62
Permanent Ineff=
       F       F       F
Bank Sta=4820,5180
XS Rating Curve= 0 ,0
Exp/Cntr=0.5,0.3

Type RM Length L Ch R = 3 ,17790   ,,,
BEGIN DESCRIPTION:
SALUDA RIVER (I-26 Ramp - TOR)
Structure ID: I-26 Ramp
Detailed Survey Structure
END DESCRIPTION:
Bridge Culvert--1,0,-1,-1, 0
Deck Dist Width WeirC Skew NumUp NumDn MinLoCord MaxHiCord MaxSubmerge Is_Ogee
32.5,35,3,0, 25, 25, , , 0.95, 0, 1,1,,
  3329.9  3354.9  3934.1  3954.1  3954.1  4059.4  4197.7  4295.9  4428.4    4545
    4680    4833    4986    5139    5257    5257    5262  5393.9  5767.8  5903.8
  6004.1    6281  6580.6  6813.7  6865.3
   208.3  207.93  220.54  220.64  220.64  221.17  220.96  219.54  215.95  211.19
  204.47   196.9  191.24  188.23  187.51  187.51  187.48  185.82  184.62  185.52
   187.1  193.61   200.6  202.94  203.05
     130     130     130     130  215.64  212.96  209.45  206.95  203.58  200.61
  197.18  193.29   189.4  185.51  182.51     130     130     130     130     130
     130     130     130     130     130
  3329.9  3354.9  3934.1  3954.1  3954.1  4059.4  4197.7  4295.9  4428.4    4545
    4680    4833    4986    5139    5257    5257    5262  5393.9  5767.8  5903.8
  6004.1    6281  6580.6  6813.7  6865.3
   208.3  207.93  220.54  220.64  220.64  221.17  220.96  219.54  215.95  211.19
  204.47   196.9  191.24  188.23  187.51  187.51  187.48  185.82  184.62  185.52
   187.1  193.61   200.6  202.94  203.05
     130     130     130     130  215.64  212.96  209.45  206.95  203.58  200.61
  197.18  193.29   189.4  185.51  182.51     130     130     130     130     130
     130     130     130     130     130
Pier Skew, UpSta & Num, DnSta & Num=  ,4059.4, 2 ,4059.4, 2 , 0 , 0 , 0 ,0,0
       5       5
   194.5  212.96
       5       5
   194.5  212.96
Pier Skew, UpSta & Num, DnSta & Num=  ,4197.7, 2 ,4197.7, 2 , 0 , 0 , 0 ,0,0
       5       5
  192.72  209.45
       5       5
  192.72  209.45
Pier Skew, UpSta & Num, DnSta & Num=  ,4295.9, 2 ,4295.9, 2 , 0 , 0 , 0 ,0,0
       5       5
     177  206.95
       5       5
     177  206.95
Pier Skew, UpSta & Num, DnSta & Num=  ,4428.4, 2 ,4428.4, 2 , 0 , 0 , 0 ,0,0
       5       5
     168  203.58
       5       5
     168  203.58
Pier Skew, UpSta & Num, DnSta & Num=  ,4545, 2 ,4545, 2 , 0 , 0 , 0 ,0,0
       5       5
     168  200.62
       5       5
     168  200.62
Pier Skew, UpSta & Num, DnSta & Num=  ,4680, 2 ,4680, 2 , 0 , 0 , 0 ,0,0
       5       5
     168  197.18
       5       5
     168  197.18
Pier Skew, UpSta & Num, DnSta & Num=  ,4833, 2 ,4833, 2 , 0 , 0 , 0 ,0,0
       5       5
     156  193.29
       5       5
     156  193.29
Pier Skew, UpSta & Num, DnSta & Num=  ,4986, 2 ,4986, 2 , 0 , 0 , 0 ,0,0
       5       5
     150   189.4
       5       5
     150   189.4
Pier Skew, UpSta & Num, DnSta & Num=  ,5139, 2 ,5139, 2 , 0 , 0 , 0 ,0,0
       5       5
     160  185.51
       5       5
     160  185.51
BR Coef= 1 , 1 , 0 ,1.25, 0 ,,,0.8,0,2,0,
WSPro=,,,, 1 ,,,, 0 ,,,, 0 ,,,,-1 ,-1 ,-1 , 0 , 0 , 0 , 0 , 0
BC Design=,, 0 ,, 0 ,,,,,,
BC HTab HWMax=205.13
BC Use User HTab Curves=0
BC User HTab FreeFlow(D)= 0

Type RM Length L Ch R = 1 ,17750   ,67,85,34
BEGIN DESCRIPTION:
SALUDA RIVER (I-26 Ramp - DS)
END DESCRIPTION:
XS GIS Cut Line= 4
      1968944.07       798454.82      1968467.06       796915.33
      1968381.51       796550.92      1967913.41       795232.68
#Sta/Elev= 30
  3388.3  208.27  3453.1  199.38  3622.1  195.35  3638.3  192.33  3655.6  185.56
  3721.3  181.41  3736.2  178.72  3797.8  176.44  3918.8  173.71  3939.8  180.09
  3955.3  173.41  3974.8  171.54  3996.8     173  4544.2     170    4720     170
    4810     166    4820     162    4870     152    4945     154    5000     150
    5065     160    5180     162  5218.6  160.15  5238.6  166.36  5258.2  168.68
  5289.6  177.18  5323.3  180.84  6053.8  188.13  6538.3  199.57  6773.2  202.35
#Mann= 4 ,-1 , 0
  3388.3     .15       0  4544.2     .06       0    4820     .04       0
    5180     .06       0
#XS Ineff= 3 ,-1
    3400    3930  207.63  3930.1    4750   185.7  5279.5    6000  184.62
Permanent Ineff=
       F       F       F
Bank Sta=4820,5180
XS Rating Curve= 0 ,0
Exp/Cntr=0.5,0.3

Type RM Length L Ch R = 1 ,17665   ,289,280,372
BEGIN DESCRIPTION:
SALUDA RIVER (I-26 - US)
END DESCRIPTION:
XS GIS Cut Line= 3
      1968995.05       798471.57      1968545.83       796947.19
      1967921.81       795215.91
#Sta/Elev= 30
  3410.8  209.19  3449.3  208.12  3499.3  199.48  3563.3  195.63  3646.7  194.05
  3706.9  190.99  3732.8  185.92    3809  180.68  3957.6  175.93  3990.3  179.95
  4007.6  172.97  4071.7  169.77  4184.8  168.06  4475.5  167.88  4599.3  170.05
  4640.4  179.64  4689.3  169.82  4800.2  167.87  4816.4     164    4825     151
    4895     152    5000     150    5105     162  5236.4     164    5245     168
  5300.6  175.27    5328   180.7    6068  187.57  6614.2  199.75  6840.3  202.19
#Mann= 4 ,-1 , 0
  3410.8     .15       0  4475.5     .15       0  4816.4     .05       0
  5236.4     .15       0
#XS Ineff= 2 , 0
       0  4641.5  180.12  5356.5       0  180.12
Permanent Ineff=
       F       F
Bank Sta=4816.4,5236.4
XS Rating Curve= 0 ,0
Exp/Cntr=0.5,0.3

Type RM Length L Ch R = 3 ,17540   ,,,
BEGIN DESCRIPTION:
SALUDA RIVER (I-26 - TOR)
Structure ID: I-26
Detailed Survey Structure
END DESCRIPTION:
Bridge Culvert--1,0,-1,-1, 0
Deck Dist Width WeirC Skew NumUp NumDn MinLoCord MaxHiCord MaxSubmerge Is_Ogee
61.5,127,3,0, 77, 77, , , 0.95, 0, 1,1,,
    3570    3617    3671    3713    3757    3804    3849    3878    3904    3939
    3975    3998    4054    4056    4077    4096    4127    4148    4169    4190
    4212    4234    4259    4280    4304    4332    4357    4383    4409    4544
    4589    4635 4653.45 4674.65 4693.67 4712.94 4746.94 4769.82 4795.25    4821
 4837.33 4858.33 4875.41 4895.79    4902  4918.7 4951.56 4970.97 5017.82 5038.22
 5045.88 5058.345090.762 5103.515116.443 5135.65 5142.075161.275 5167.73 5174.19
 5186.83 5194.285201.7245207.273 5219.21 5232.05 5244.78 5257.39    5281 5291.69
 5315.225336.069    5399    5513    5606    5735    5935
     215     214     213     212     211     210     209 208.497  207.87 207.048
 205.965 205.336 203.447     203     202     201     200     199     198     197
     196     195     194     193     192     191     190     189     188     185
     184 183.136 182.811 182.456 182.175 181.861 181.361 181.122 180.859 180.673
  180.55 180.411 180.332 180.247   180.2 180.157 180.115 180.136 180.159 180.246
 180.268 180.331 180.459 180.521 180.598 180.726 180.743 180.791 180.839 180.887
 180.902 180.942 180.983  180.99     181  181.07  181.17  181.25 181.447 181.467
  181.62 181.659     182     183     184     185     186
                                                                                
                                                                                
                                                                                
         179.841 179.516 179.161  178.88 178.566 178.066 177.827 177.564 177.378
 177.255 177.116 177.037 176.952 176.905 176.862  176.82 176.841 176.864 176.951
 176.973 177.036 177.164 177.226 177.303 177.431 177.448 177.496 177.544 177.592
 177.607 177.647 177.688 177.695 177.705 177.775 177.875 177.955 178.152 178.172
 178.325 178.364
    3570    3617    3671    3713    3757    3804    3849    3878    3904    3939
    3975    3998    4054    4056    4077    4096    4127    4148    4169    4190
    4212    4234    4259    4280    4304    4332    4357    4383    4409    4544
    4589    4635 4653.45 4674.65 4693.67 4712.94 4746.94 4769.82 4795.25    4821
 4837.33 4858.33 4875.41 4895.79    4902  4918.7 4951.56 4970.97 5017.82 5038.22
 5045.88 5058.345090.762 5103.515116.443 5135.65 5142.075161.275 5167.73 5174.19
 5186.83 5194.285201.7245207.273 5219.21 5232.05 5244.78 5257.39    5281 5291.69
 5315.225336.069    5399    5513    5606    5735    5935
     215     214     213     212     211     210     209 208.497  207.87 207.048
 205.965 205.336 203.447     203     202     201     200     199     198     197
     196     195     194     193     192     191     190     189     188     185
     184 183.136 182.811 182.456 182.175 181.861 181.361 181.122 180.859 180.673
  180.55 180.411 180.332 180.247   180.2 180.157 180.115 180.136 180.159 180.246
 180.268 180.331 180.459 180.521 180.598 180.726 180.743 180.791 180.839 180.887
 180.902 180.942 180.983  180.99     181  181.07  181.17  181.25 181.447 181.467
  181.62 181.659     182     183     184     185     186
                                                                                
                                                                                
                                                                                
         179.841 179.516 179.161  178.88 178.566 178.066 177.827 177.564 177.378
 177.255 177.116 177.037 176.952 176.905 176.862  176.82 176.841 176.864 176.951
 176.973 177.036 177.164 177.226 177.303 177.431 177.448 177.496 177.544 177.592
 177.607 177.647 177.688 177.695 177.705 177.775 177.875 177.955 178.152 178.172
 178.325 178.364
Pier Skew, UpSta & Num, DnSta & Num=  ,4685, 2 ,4685, 2 , 0 , 0 , 0 ,0,0
       4       4
   163.5  178.86
       4       4
   163.5  178.86
Pier Skew, UpSta & Num, DnSta & Num=  ,4755, 2 ,4755, 2 , 0 , 0 , 0 ,0,0
       4       4
     163  178.72
       4       4
     163  178.72
Pier Skew, UpSta & Num, DnSta & Num=  ,4825, 2 ,4825, 2 , 0 , 0 , 0 ,0,0
       4       4
     149  178.57
       4       4
     149  178.57
Pier Skew, UpSta & Num, DnSta & Num=  ,4895, 2 ,4895, 2 , 0 , 0 , 0 ,0,0
       4       4
     150  178.43
       4       4
     150  178.43
Pier Skew, UpSta & Num, DnSta & Num=  ,4965, 2 ,4965, 2 , 0 , 0 , 0 ,0,0
       4       4
   148.5  178.28
       4       4
   148.5  178.28
Pier Skew, UpSta & Num, DnSta & Num=  ,5035, 2 ,5035, 2 , 0 , 0 , 0 ,0,0
       4       4
     153  178.14
       4       4
     153  178.14
Pier Skew, UpSta & Num, DnSta & Num=  ,5105, 2 ,5105, 2 , 0 , 0 , 0 ,0,0
       4       4
     160     178
       4       4
     160     178
Pier Skew, UpSta & Num, DnSta & Num=  ,5175, 2 ,5175, 2 , 0 , 0 , 0 ,0,0
       4       4
     158  177.85
       4       4
     158  177.85
Pier Skew, UpSta & Num, DnSta & Num=  ,5245, 2 ,5245, 2 , 0 , 0 , 0 ,0,0
       4       4
     166  177.71
       4       4
     166  177.71
BR Coef= 1 , 1 , 0 ,1.25, 0 ,,,0.8,0,2,0,
WSPro=,,,, 1 ,,,, 0 ,,,, 0 ,,,,-1 ,-1 ,-1 , 0 , 0 , 0 , 0 , 0
BC Design=,, 0 ,, 0 ,,,,,,
BC HTab HWMax=209.19
BC Use User HTab Curves=0
BC User HTab FreeFlow(D)= 0

Type RM Length L Ch R = 1 ,17385   ,306,385,416
BEGIN DESCRIPTION:
SALUDA RIVER (I-26 - DS)
END DESCRIPTION:
XS GIS Cut Line= 3
      1969350.99       798187.76      1968803.81         797056.
       1968156.7       795248.87
#Sta/Elev= 30
  3742.9  210.41  3774.9  210.03  3813.7  214.91  3843.2  214.07  3874.1  209.05
    3909  200.17  3979.5  187.38  4060.3  181.15  4362.4  170.73  4816.4     164
    4825     151    5000     150    5105     162    5175     160  5236.4     164
    5245     168  5399.2  200.73  5410.6  203.27  5616.7   210.4  5778.9  210.87
  5839.7  208.89  6079.7  178.85    6182  176.26  6224.5  172.35  6295.6  178.75
  6337.1  179.49    6530  193.21  6673.3  217.46    6793  225.75  6919.5  234.51
#Mann= 6 ,-1 , 0
  3742.9     .06       0  3874.1     .15       0  4816.4     .05       0
  5236.4     .15       0  5399.2      .1       0    6793     .11       0
#XS Ineff= 2 , 0
       0  4543.5  180.12  5386.5       0  180.12
Permanent Ineff=
       F       F
Bank Sta=4816.4,5236.4
XS Rating Curve= 0 ,0
Exp/Cntr=0.5,0.3