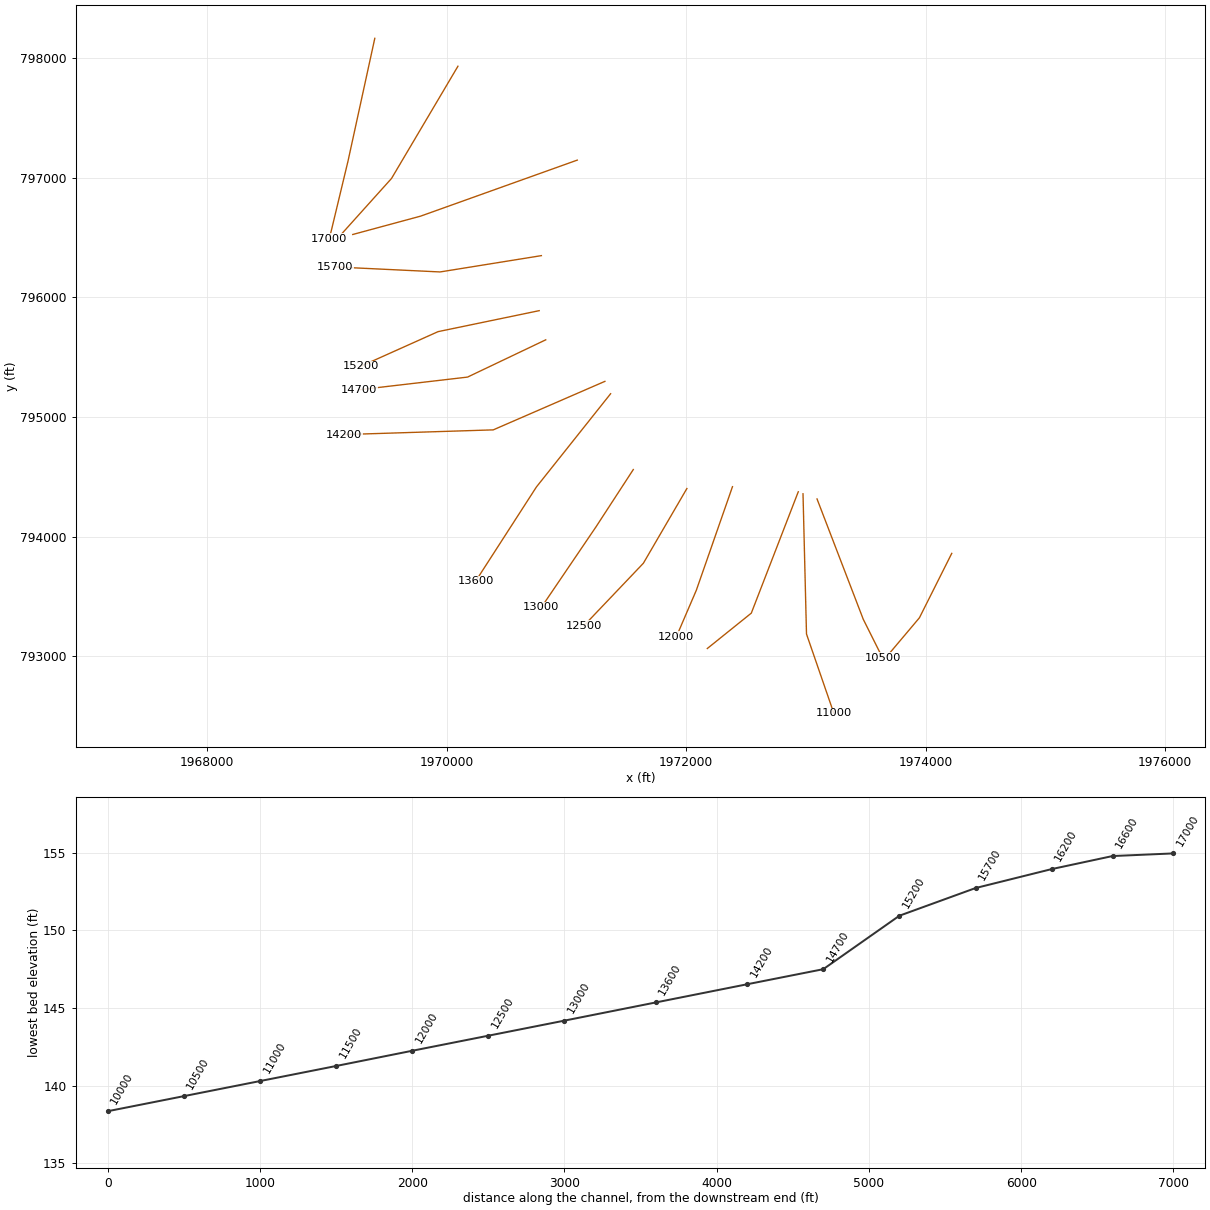
HEC-RAS study CCR_Prelim_Updated.prj: CCR SALUDA RIVER Detailed Study

--- CCR_Prelim_Updated.g03 (geometry) --- (continued)

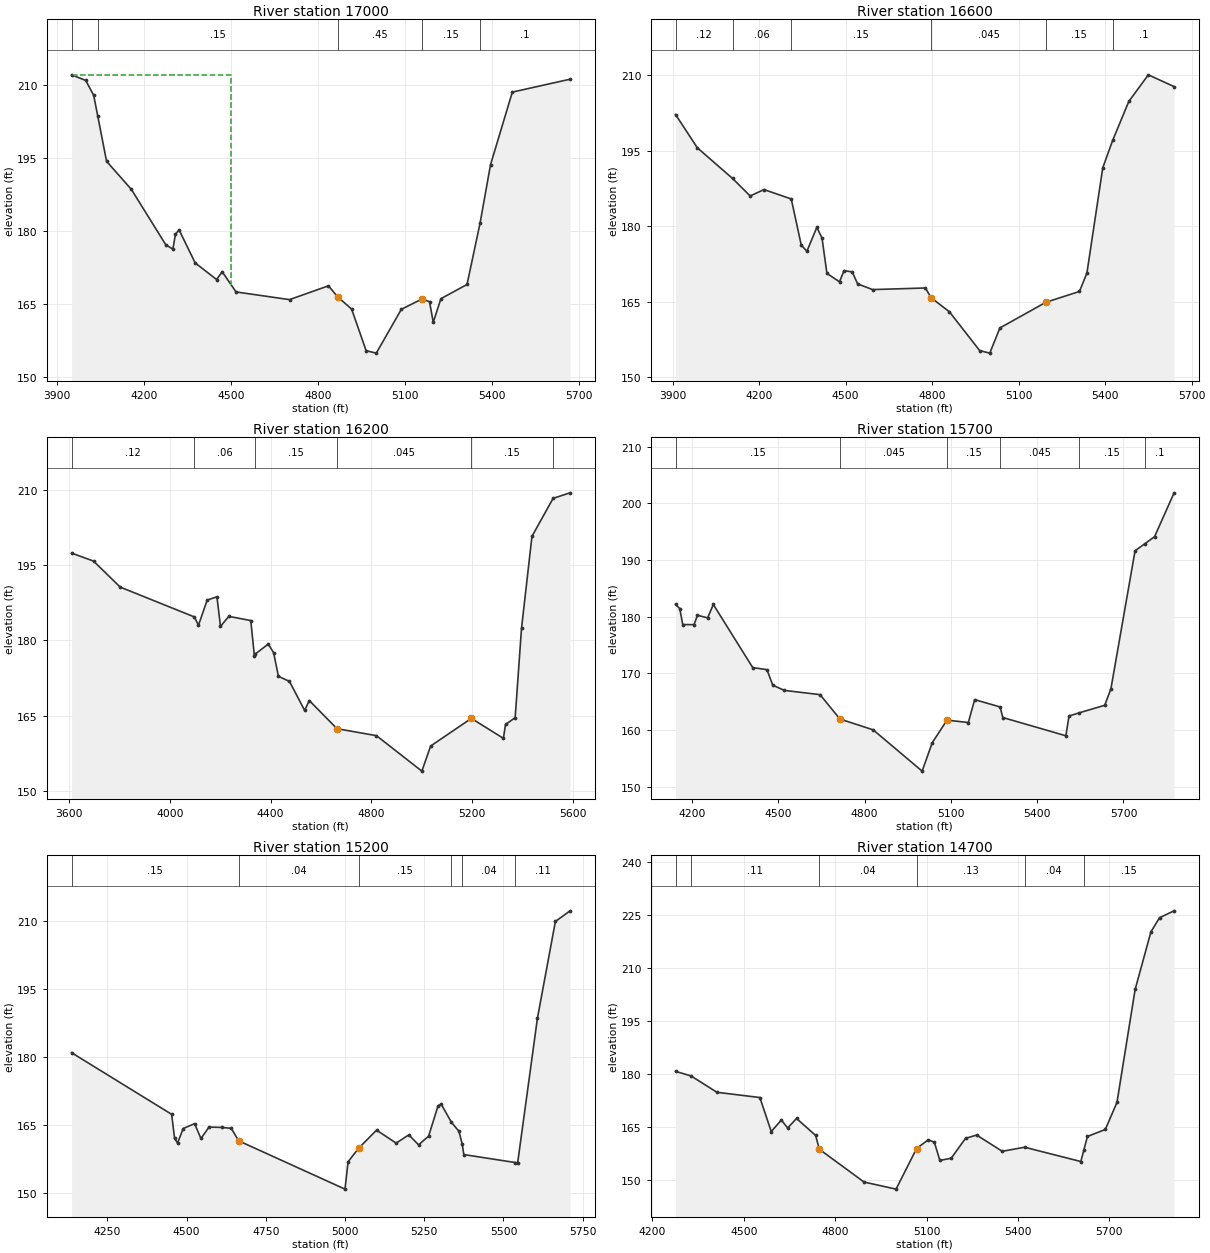
Type RM Length L Ch R = 1 ,17000   ,500,400,251
BEGIN DESCRIPTION:
SALUDA RIVER 37.0
END DESCRIPTION:
XS GIS Cut Line= 3
       1969399.2       798164.06      1969175.35       797137.59
      1969019.47       796487.82
#Sta/Elev= 30
  3949.4  212.12    3998  210.97  4025.6  207.92  4039.3  203.74    4070  194.36
  4155.6  188.58  4274.1  177.22  4298.6  176.31  4307.5  179.34  4319.8  180.29
  4375.6  173.48  4449.4  170.07  4468.6  171.67  4516.5  167.52  4700.9  165.94
  4835.1  168.78  4866.8  166.51    4915     164    4965  155.45    5000  154.95
  5086.4  163.95  5158.2  166.09  5183.6  165.51  5196.4  161.28  5222.9  166.14
  5312.9  169.05  5358.1  181.73  5393.9  193.66  5469.1  208.57  5668.2  211.22
#Mann= 5 ,-1 , 0
  3949.4     .06       0  4039.3     .15       0  4866.8     .45       0
  5158.2     .15       0  5358.1      .1       0
#XS Ineff= 2 , 0
       0    4500     212               0
Permanent Ineff=
       F       F
Bank Sta=4866.8,5158.2
XS Rating Curve= 0 ,0
Exp/Cntr=0.3,0.1

Type RM Length L Ch R = 1 ,16600   ,671,400,215
BEGIN DESCRIPTION:
SALUDA RIVER 36.0
END DESCRIPTION:
XS GIS Cut Line= 3
       1970093.6       797930.83      1969538.96       796992.96
      1969111.71       796517.66
#Sta/Elev= 30
  3910.4   202.2  3985.7   195.6  4107.9   189.5    4169  186.02    4217  187.29
  4311.5  185.43  4346.1  176.28  4365.7  175.02  4400.2  179.78  4418.2  177.65
  4435.2  170.63  4478.9  168.95  4494.5  171.18  4522.9  170.93  4541.7  168.54
  4593.5  167.41  4776.9  167.73  4796.2   165.8    4860     163    4965  155.28
    5000  154.78    5035  159.78  5194.6  164.89    5311  167.04  5336.9  170.72
  5391.8  191.62  5426.1  197.06  5482.1  204.81  5549.8   210.1  5639.1  207.76
#Mann= 6 ,-1 , 0
  3910.4     .12       0  4107.9     .06       0  4311.5     .15       0
  4796.2    .045       0  5194.6     .15       0  5426.1      .1       0
Bank Sta=4796.2,5194.6
XS Rating Curve= 0 ,0
Exp/Cntr=0.3,0.1

Type RM Length L Ch R = 1 ,16200   ,568,500,361
BEGIN DESCRIPTION:
SALUDA RIVER 35.0
END DESCRIPTION:
XS GIS Cut Line= 3
      1971090.43       797146.26      1969782.51       796678.06
      1969215.04       796524.44
#Sta/Elev= 30
  3610.8  197.35  3697.8  195.76  3803.7  190.58  4097.7  184.64    4114  182.99
  4148.6     188  4187.3  188.65  4201.4  182.75  4234.3  184.75  4321.5  183.92
  4335.8  176.91  4339.7  177.28  4390.9  179.24  4412.2  177.51  4431.1  172.82
    4475   171.8  4535.1  166.03  4553.5     168  4663.5  162.39    4820     161
    5000  153.94    5035  158.94  5196.4  164.44  5323.4  160.47  5331.9  163.23
  5370.1  164.58  5395.3  182.36  5436.7  200.68  5520.6  208.25  5587.9  209.35
#Mann= 6 ,-1 , 0
  3610.8     .12       0  4097.7     .06       0  4339.7     .15       0
  4663.5    .045       0  5196.4     .15       0  5520.6      .1       0
Bank Sta=4663.5,5196.4
XS Rating Curve= 0 ,0
Exp/Cntr=0.3,0.1

Type RM Length L Ch R = 1 ,15700   ,479,500,875
BEGIN DESCRIPTION:
SALUDA RIVER 34.0
END DESCRIPTION:
XS GIS Cut Line= 3
      1970790.53       796347.75      1969944.34       796211.38
      1969069.45       796253.32
#Sta/Elev= 30
  4142.9  182.14  4157.4  181.41  4167.8  178.59  4206.9  178.57    4219  180.23
  4254.3  179.77  4274.1  182.13  4411.1  170.99  4460.4  170.63  4480.9  167.88
    4521  166.97  4645.1  166.22  4714.1  161.92    4830     160    5000  152.72
    5035  157.72  5086.4  161.72  5160.6   161.3  5182.6  165.34  5270.9  164.05
  5280.6  162.18  5499.7  158.96  5510.6  162.45  5546.1  163.01  5634.8  164.34
  5656.4  167.27  5740.3  191.62  5773.3  192.82    5808  194.09  5875.9  201.84
#Mann= 6 ,-1 , 0
  4142.9     .15       0  4714.1    .045       0  5086.4     .15       0
  5270.9    .045       0  5546.1     .15       0  5773.3      .1       0
Bank Sta=4714.1,5086.4
XS Rating Curve= 0 ,0
Exp/Cntr=0.3,0.1

Type RM Length L Ch R = 1 ,15200   ,373,500,257
BEGIN DESCRIPTION:
SALUDA RIVER 33.0
END DESCRIPTION:
XS GIS Cut Line= 3
      1970772.22       795887.77      1969927.54        795712.4
      1969279.56       795421.69
#Sta/Elev= 30
  4137.3  180.98    4453  167.41  4462.3  162.13  4471.6  161.07  4489.4  164.28
  4525.4  165.36  4545.5  162.09  4570.8   164.6  4610.8  164.53    4641  164.33
  4664.7  161.57    5000  150.94  5009.7  156.96    5043  159.94  5099.6  163.93
  5161.5  161.07  5201.4  162.89  5232.2  160.69  5263.8   162.6  5293.8  169.31
  5303.6  169.64  5335.6  165.68  5359.6  163.67    5370  160.81  5374.9  158.55
    5537   156.8  5544.8  156.72  5607.1  188.53  5663.9  209.88  5710.2  212.22
#Mann= 6 ,-1 , 0
  4137.3     .15       0  4664.7     .04       0    5043     .15       0
  5335.6     .11       0    5370     .04       0    5537     .11       0
Bank Sta=4664.7,5043
XS Rating Curve= 0 ,0
Exp/Cntr=0.3,0.1

Type RM Length L Ch R = 1 ,14700   ,508,500,394
BEGIN DESCRIPTION:
SALUDA RIVER 32.0
END DESCRIPTION:
XS GIS Cut Line= 3
       1970827.1        795644.1      1970173.87       795332.59
      1969267.43       795226.75
#Sta/Elev= 30
  4276.3  180.81  4326.7  179.53  4412.2  174.89  4552.9  173.41  4590.3  163.79
  4623.5  167.05  4644.1  164.79  4673.3  167.48    4736  162.69  4748.1  158.78
    4895   149.5    5000   147.5  5067.4  158.99  5105.6  161.45  5125.8  160.76
  5143.7  155.61  5181.1  156.25    5228  161.86  5264.6  162.79  5348.6   158.2
    5422  159.35  5606.5  155.31  5616.8  158.68  5628.2   162.4  5686.9  164.37
  5725.2  172.04  5784.8  203.98  5836.5  220.25  5864.8  224.27  5912.6  226.22
#Mann= 6 ,-1 , 0
  4276.3     .15       0  4326.7     .11       0  4748.1     .04       0
  5067.4     .13       0    5422     .04       0  5616.8     .15       0
Bank Sta=4748.1,5067.4
XS Rating Curve= 0 ,0
Exp/Cntr=0.3,0.1

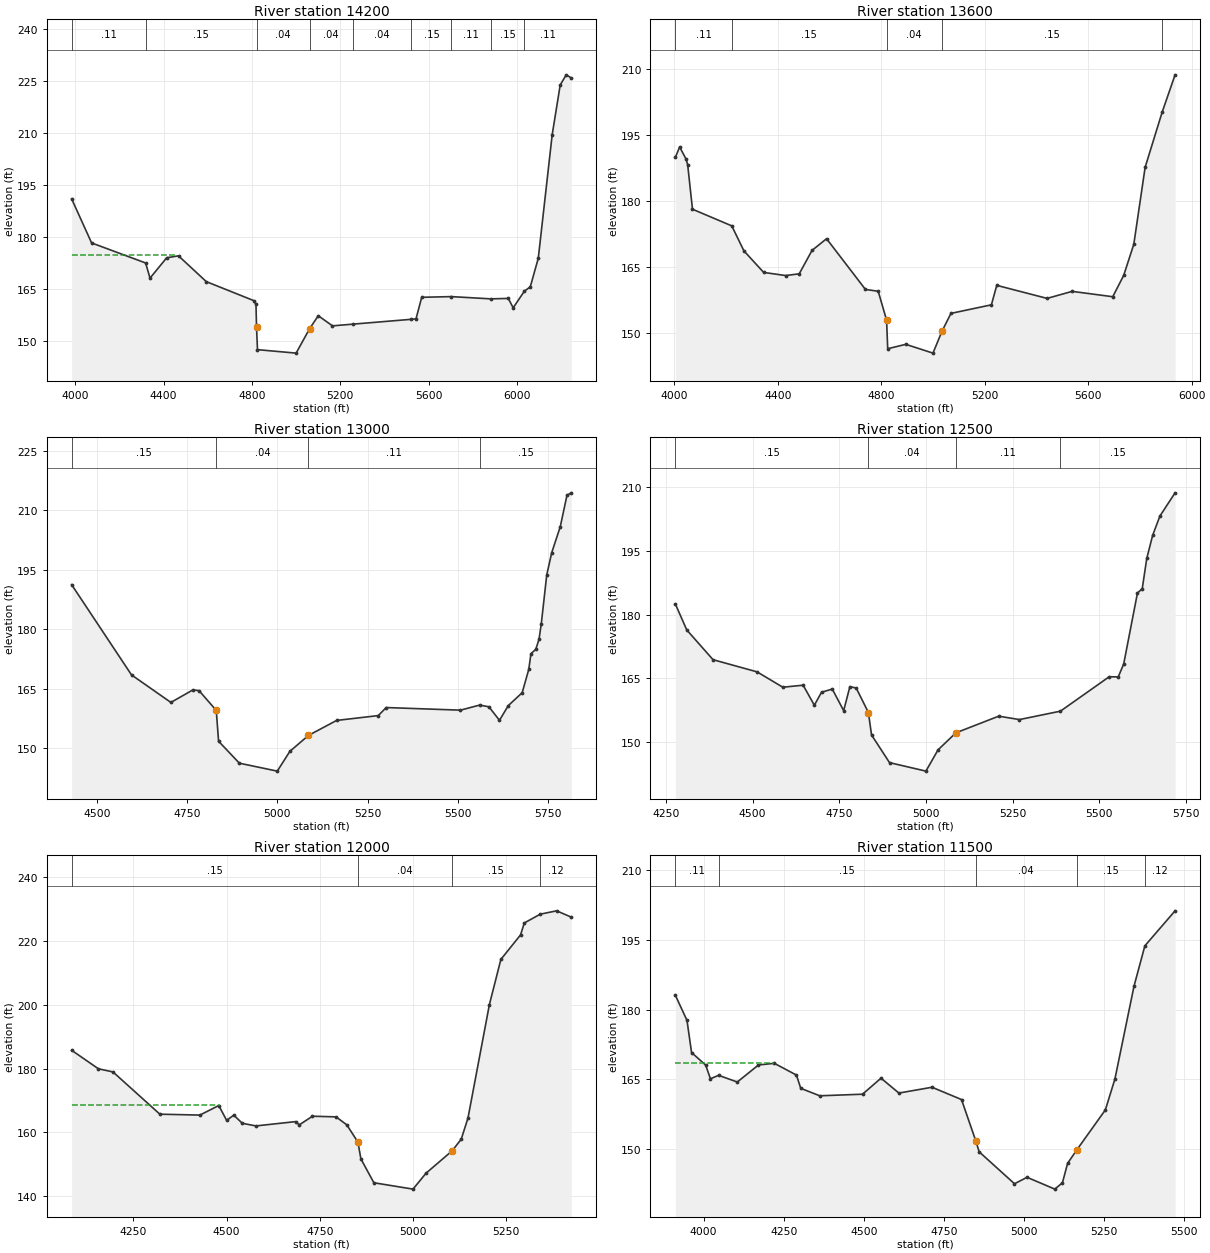
Type RM Length L Ch R = 1 ,14200   ,494,600,1335
BEGIN DESCRIPTION:
SALUDA RIVER 31.0
END DESCRIPTION:
XS GIS Cut Line= 3
      1971321.04       795296.85      1970388.47       794891.38
      1969142.49       794852.07
#Sta/Elev= 30
  3983.1  190.99  4073.5  178.29  4318.3  172.51  4338.1  168.14  4413.6  174.01
  4467.2  174.57    4593  167.14  4807.5  161.68  4818.2  160.61  4820.7  154.03
    4825  147.53    5000  146.53  5060.7  153.53  5100.4  157.31  5164.8  154.39
  5256.7  154.88  5522.6  156.28  5543.1  156.39    5569  162.62  5703.4  162.82
  5881.9  162.17  5961.3   162.3  5983.3  159.59    6034  164.38  6060.8  165.63
  6097.1  173.88  6160.2  209.53  6196.4  223.81  6223.7  226.74  6246.6  225.84
#Mann= 9 ,-1 , 0
  3983.1     .11       0  4318.3     .15       0  4820.7     .04       0
  5060.7     .04       0  5256.7     .04       0  5522.6     .15       0
  5703.4     .11       0  5881.9     .15       0    6034     .11       0
#XS Ineff= 2 , 0
       0    4450   174.7               0
Permanent Ineff=
       F       F
Bank Sta=4820.7,5060.7
XS Rating Curve= 0 ,0
Exp/Cntr=0.3,0.1

Type RM Length L Ch R = 1 ,13600   ,580,600,593
BEGIN DESCRIPTION:
SALUDA RIVER 30.0
END DESCRIPTION:
XS GIS Cut Line= 3
       1971368.8       795193.44      1970749.15       794414.17
      1970242.17       793627.48
#Sta/Elev= 30
  4004.4  189.92  4020.6  192.26  4045.2  189.54  4051.7  188.23  4070.3   178.1
  4222.2  174.31  4269.1  168.63  4345.5  163.72  4430.4  163.01  4482.9   163.4
  4532.5  168.73  4588.6  171.39  4738.9  159.85  4788.3  159.43  4820.7  152.86
    4825  146.36    4895  147.36    5000  145.36    5035  150.36  5069.5   154.4
  5225.9  156.35  5246.6  160.78  5441.2  157.81    5538  159.41    5695  158.19
  5737.3  163.04  5776.4  170.13  5820.2  187.64  5885.9  200.16  5935.9  208.67
#Mann= 5 ,-1 , 0
  4004.4     .11       0  4222.2     .15       0  4820.7     .04       0
    5035     .15       0  5885.9     .12       0
Bank Sta=4820.7,5035
XS Rating Curve= 0 ,0
Exp/Cntr=0.3,0.1

Type RM Length L Ch R = 1 ,13000   ,486,500,423
BEGIN DESCRIPTION:
SALUDA RIVER 29.0
END DESCRIPTION:
XS GIS Cut Line= 3
      1971558.15       794559.65      1971247.65       794082.11
      1970790.48       793408.14
#Sta/Elev= 30
  4430.4  191.19  4596.2  168.45  4705.3  161.51  4766.3  164.67  4783.4  164.47
    4831   159.5  4837.4  151.73    4895  146.19    5000  144.19    5035  149.19
  5086.4  153.19  5164.4  156.97  5279.7  158.19  5301.8  160.22  5507.4  159.56
  5560.6  160.84  5586.2  160.41  5615.5     157  5639.9  160.71  5678.4  163.96
  5696.6  169.83  5702.7   173.8  5716.1   174.9    5725  177.43  5731.2  181.24
  5746.4  193.64  5760.1  199.23  5783.9  205.82  5802.4  213.71  5814.4  214.35
#Mann= 4 ,-1 , 0
  4430.4     .15       0    4831     .04       0  5086.4     .11       0
  5560.6     .15       0
Bank Sta=4831,5086.4
XS Rating Curve= 0 ,0
Exp/Cntr=0.3,0.1

Type RM Length L Ch R = 1 ,12500   ,455,500,763
BEGIN DESCRIPTION:
SALUDA RIVER 28.0
END DESCRIPTION:
XS GIS Cut Line= 3
      1972005.95       794401.26      1971642.46       793776.63
      1971146.88       793255.84
#Sta/Elev= 30
  4277.3  182.48    4310  176.41  4385.8  169.42  4512.8  166.56  4587.1  162.95
  4645.8  163.42  4678.1  158.71  4698.8  161.76  4729.8  162.52  4762.7  157.44
  4780.6  163.07  4798.8  162.77  4834.1     157  4843.1  151.73    4895  145.22
    5000  143.22    5035  148.22  5086.4  152.22  5210.1  156.14  5269.9  155.34
  5388.2  157.32  5528.9  165.41    5555  165.37  5570.7  168.42  5610.4   185.1
  5624.2  186.11  5637.2  193.21  5654.1  198.62  5675.1  203.18  5718.9  208.65
#Mann= 4 ,-1 , 0
  4277.3     .15       0  4834.1     .04       0  5086.4     .11       0
  5388.2     .15       0
Bank Sta=4834.1,5086.4
XS Rating Curve= 0 ,0
Exp/Cntr=0.3,0.1

Type RM Length L Ch R = 1 ,12000   ,505,500,406
BEGIN DESCRIPTION:
SALUDA RIVER 27.0
END DESCRIPTION:
XS GIS Cut Line= 3
      1972386.71       794416.48      1972085.09       793551.67
      1971917.58        793161.4
#Sta/Elev= 30
  4084.1  185.77  4155.9  179.97    4195  178.98  4320.8  165.74  4428.3  165.46
  4478.8  168.45    4500  163.81  4519.2  165.43    4542  162.89  4578.5  162.06
  4684.8  163.41  4695.1  162.41  4730.3   165.1  4793.6   164.9  4822.5  162.38
  4852.3  156.96  4860.2  151.73    4895  144.25    5000  142.25    5035  147.25
    5105  154.25  5129.4   157.9  5147.5  164.52    5205   200.1  5235.8  214.26
  5288.6  221.94  5298.7  225.68  5341.5  228.43  5385.4  229.48  5424.7   227.5
#Mann= 4 ,-1 , 0
  4084.1     .15       0  4852.3     .04       0    5105     .15       0
  5341.5     .12       0
#XS Ineff= 2 , 0
       0    4480   168.7               0
Permanent Ineff=
       F       F
Bank Sta=4852.3,5105
XS Rating Curve= 0 ,0
Exp/Cntr=0.3,0.1

Type RM Length L Ch R = 1 ,11500   ,384,500,897
BEGIN DESCRIPTION:
SALUDA RIVER 26.0
END DESCRIPTION:
XS GIS Cut Line= 3
      1972936.22       794374.07      1972543.94       793359.57
       1972176.5       793063.94
#Sta/Elev= 30
  3912.3  183.05  3948.4  177.66  3962.6  170.73  4006.8  168.01  4021.5  165.07
    4047  165.81  4105.4  164.37  4171.5  168.05    4221   168.4  4289.9  165.87
  4303.4  163.01  4362.7   161.4  4496.2  161.74  4553.9   165.2  4609.7  161.99
  4713.1  163.24  4805.1  160.59  4849.4  151.73  4860.2  149.32  4970.4  142.43
  5009.7  143.82  5096.4  141.27  5120.1  142.65  5136.2  146.83    5165  149.74
  5254.1  158.36  5283.9  165.03  5343.6  185.08  5377.4  193.75  5471.6  201.29
#Mann= 5 ,-1 , 0
  3912.3     .11       0    4047     .15       0  4849.4     .04       0
    5165     .15       0  5377.4     .12       0
#XS Ineff= 2 , 0
       0    4220  168.42               0
Permanent Ineff=
       F       F
Bank Sta=4849.4,5165
XS Rating Curve= 0 ,0
Exp/Cntr=0.3,0.1

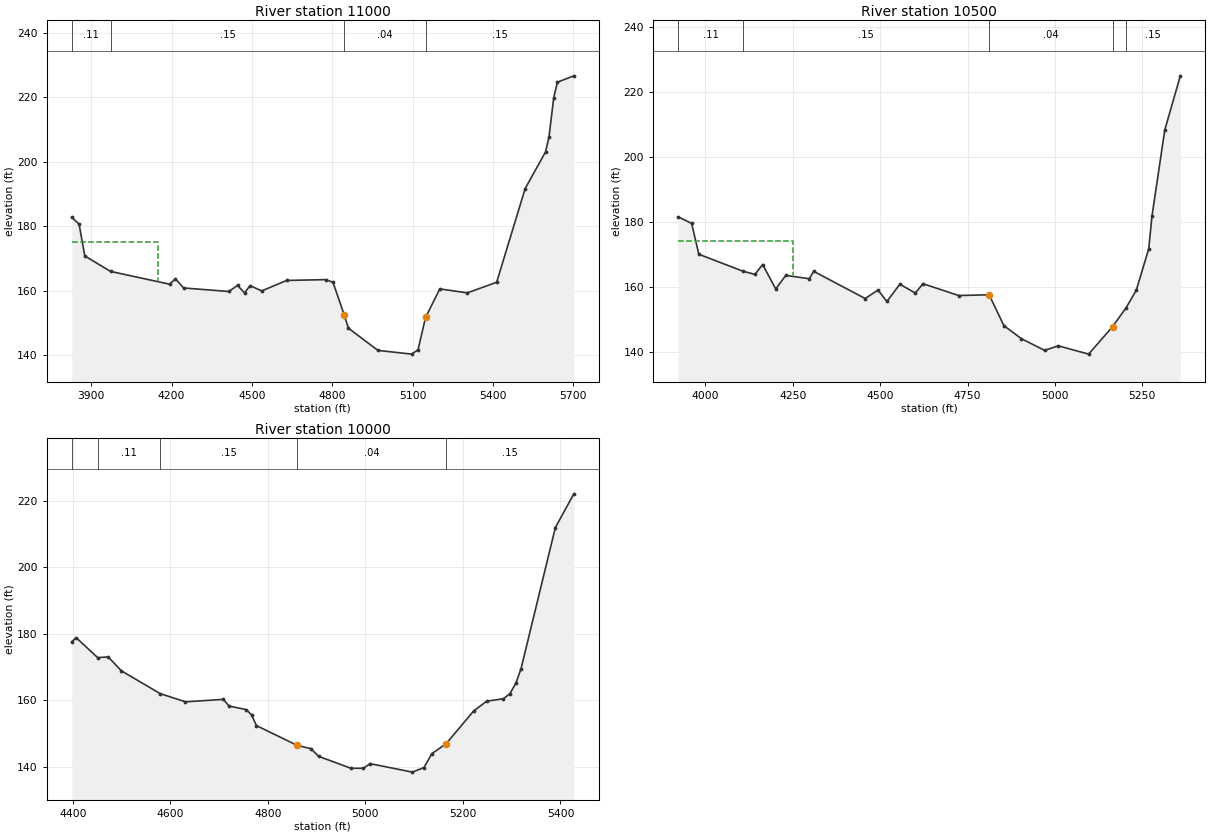
Type RM Length L Ch R = 1 ,11000   ,398,500,523
BEGIN DESCRIPTION:
SALUDA RIVER 25.0
END DESCRIPTION:
XS GIS Cut Line= 3
       1972975.8       794356.93      1973004.91       793184.99
      1973233.56       792521.69
#Sta/Elev= 30
  3827.7  182.72  3854.9  180.67  3876.3  170.78  3972.5  165.97  4192.6  162.01
  4214.7  163.63  4245.6  160.83  4413.8  159.74  4446.3  161.62  4472.5   159.3
  4493.2  161.56  4536.5  159.92    4630  163.17    4776  163.42  4802.8  162.57
  4844.6  152.46  4860.2  148.35  4970.4  141.46  5096.4   140.3  5120.1  141.68
  5148.1  151.67  5201.3  160.54  5303.9  159.31  5413.5   162.6  5519.8  191.66
    5596  203.07  5608.8  207.69  5626.5  219.87  5640.3  224.69  5701.6  226.67
#Mann= 4 ,-1 , 0
  3827.7     .11       0  3972.5     .15       0  4844.6     .04       0
  5148.1     .15       0
#XS Ineff= 2 , 0
       0    4150     175               0
Permanent Ineff=
       F       F
Bank Sta=4844.6,5148.1
XS Rating Curve= 0 ,0
Exp/Cntr=0.3,0.1

Type RM Length L Ch R = 1 ,10500   ,779,500,198
BEGIN DESCRIPTION:
SALUDA RIVER 24.0
END DESCRIPTION:
XS GIS Cut Line= 3
       1973092.9       794313.93      1973478.94       793308.39
      1973639.32       792987.76
#Sta/Elev= 30
  3922.9  181.53  3961.2   179.5  3981.8  170.03  4107.9  164.82  4142.1  163.84
  4164.2  166.86  4201.7  159.38  4230.5  163.53  4297.9  162.51    4310  164.79
  4457.5  156.42    4494  159.04  4519.5  155.51  4556.5  160.81  4600.9  158.11
  4622.6  160.98  4724.8  157.34  4811.8  157.58  4854.1  148.08  4904.1  144.08
  4970.4  140.49  5009.7  141.88  5096.4  139.33    5165   147.8  5203.9  153.65
  5232.6  158.96  5268.2  171.72  5277.5  181.76    5314  208.19  5358.5  224.88
#Mann= 5 ,-1 , 0
  3922.9     .11       0  4107.9     .15       0  4811.8     .04       0
    5165     .15       0  5203.9     .15       0
#XS Ineff= 2 , 0
       0    4250     174               0
Permanent Ineff=
       F       F
Bank Sta=4811.8,5165
XS Rating Curve= 0 ,0
Exp/Cntr=0.3,0.1

Type RM Length L Ch R = 1 ,10000   ,530,500,501
BEGIN DESCRIPTION:
SALUDA RIVER 23.0
END DESCRIPTION:
XS GIS Cut Line= 3
      1974218.09       793859.03      1973948.16       793320.82
      1973672.84       792993.92
#Sta/Elev= 30
  4397.9  177.61  4406.9  178.86    4451  172.84  4472.6  173.06  4499.8  168.85
  4579.2     162  4631.1  159.53  4708.7  160.27  4720.7  158.24  4755.5   157.2
  4766.5  155.61  4776.5  152.38  4860.2  146.41  4888.2  145.43  4904.1  143.11
  4970.4  139.52  4995.9  139.52  5009.7  140.91  5096.4  138.36  5120.1  139.74
  5136.2  143.92    5165  146.83  5222.1   156.8    5249  159.74  5282.9  160.44
  5296.4  162.01  5308.7  165.22  5319.1   169.5  5389.5  212.01  5427.4  222.17
#Mann= 5 ,-1 , 0
  4397.9     .06       0    4451     .11       0  4579.2     .15       0
  4860.2     .04       0    5165     .15       0
Bank Sta=4860.2,5165
XS Rating Curve= 0 ,0
Exp/Cntr=0.3,0.1