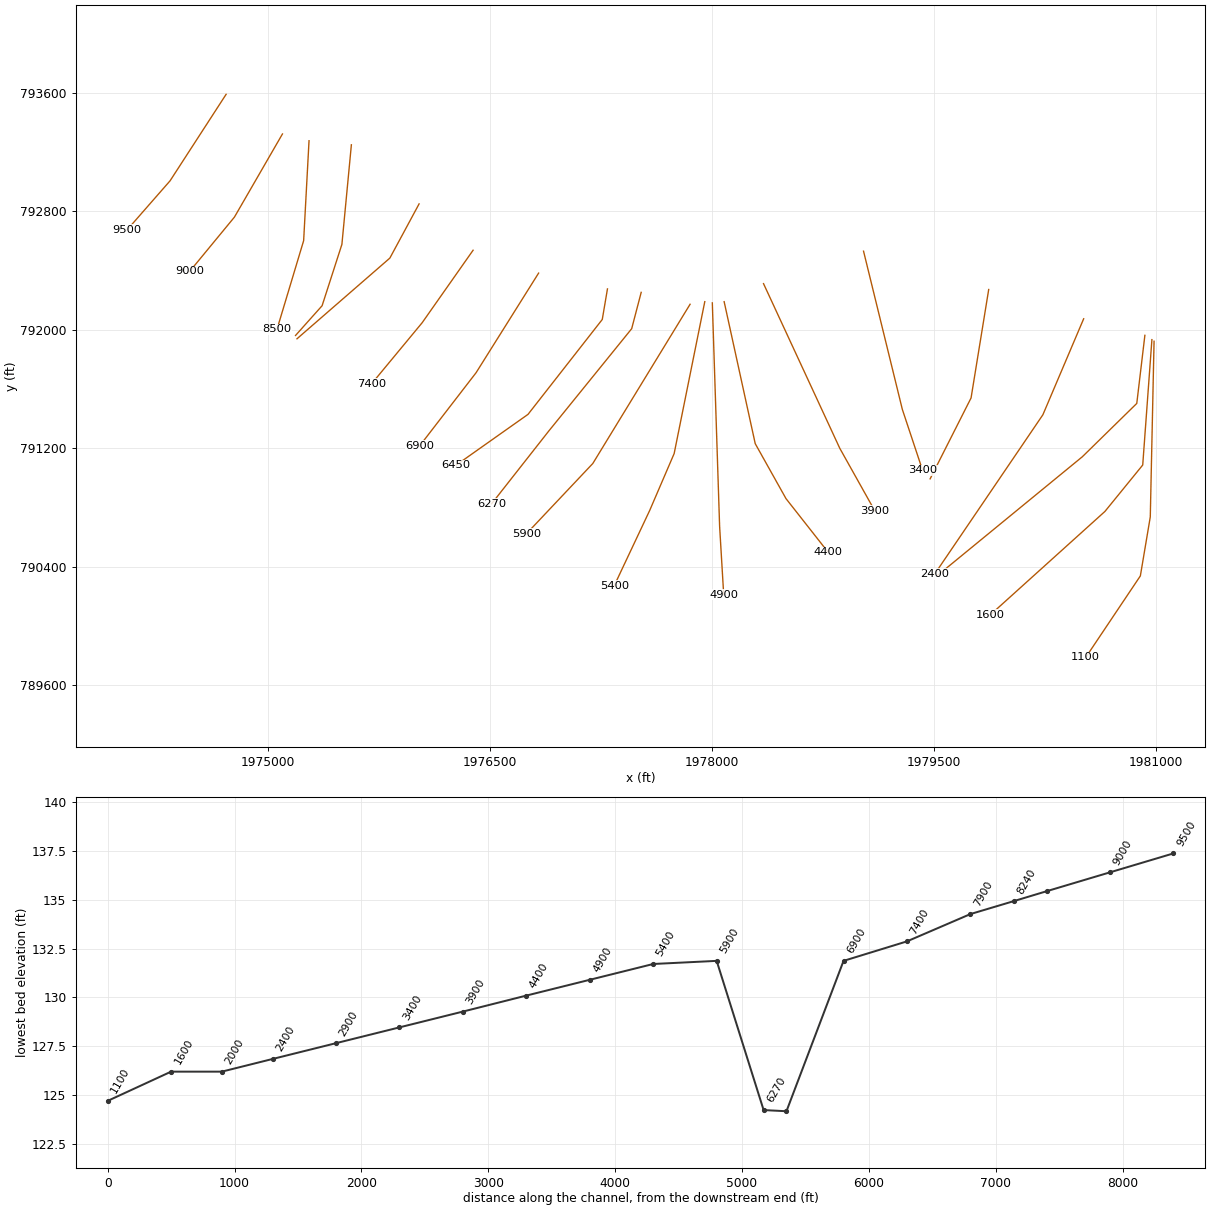
HEC-RAS study CCR_Prelim_Updated.prj: CCR SALUDA RIVER Detailed Study

--- CCR_Prelim_Updated.g03 (geometry) --- (continued)

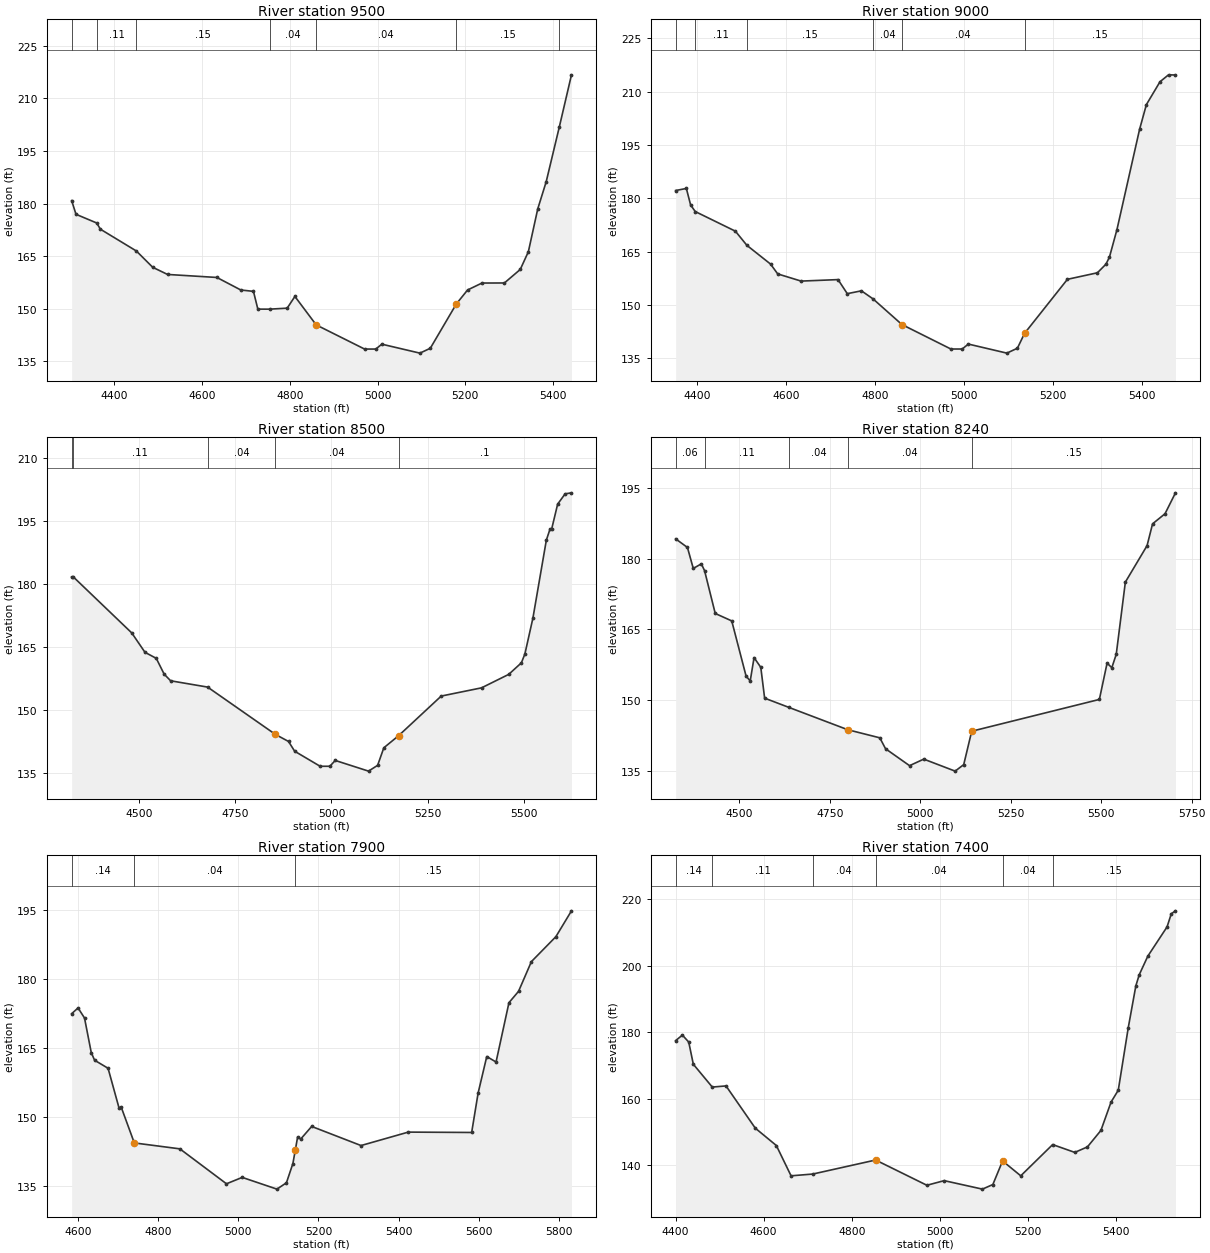
Type RM Length L Ch R = 1 ,9500    ,484,500,500
BEGIN DESCRIPTION:
SALUDA RIVER 22.0
END DESCRIPTION:
XS GIS Cut Line= 3
      1974714.62       793590.97       1974335.5       793006.34
      1974044.47       792674.07
#Sta/Elev= 30
  4303.2  180.84  4313.1  176.94  4360.3  174.46  4368.6   172.7  4450.6  166.48
  4487.8  161.84  4521.6   159.8    4634  158.94  4688.5  155.37  4717.3  154.98
  4727.3  149.92  4754.1  149.91  4794.1  150.19  4811.7  153.53  4860.2  145.43
  4970.4  138.54  4995.9  138.54  5009.7  139.93  5096.4  137.38  5120.1  138.76
  5179.5  151.41    5205  155.37  5237.8  157.35  5288.9  157.37    5325  161.22
  5343.5  166.28  5364.9   178.5  5384.1  186.22    5414  201.83  5441.7  216.68
#Mann= 7 ,-1 , 0
  4303.2     .06       0  4360.3     .11       0  4450.6     .15       0
  4754.1     .04       0  4860.2     .04       0  5179.5     .15       0
    5414     .12       0
Bank Sta=4860.2,5179.5
XS Rating Curve= 0 ,0
Exp/Cntr=0.3,0.1

Type RM Length L Ch R = 1 ,9000    ,299,500,620
BEGIN DESCRIPTION:
SALUDA RIVER 21.0
END DESCRIPTION:
XS GIS Cut Line= 3
       1975095.4       793322.92      1974770.61       792760.92
      1974467.84       792393.76
#Sta/Elev= 30
  4350.9  182.19    4375  182.77  4384.6  178.12    4395  176.27  4485.4  170.74
  4511.3  166.75  4564.5  161.48  4580.6  158.71  4633.3  156.69  4716.4  157.11
  4737.2  153.15    4769  153.95  4795.2  151.68  4860.2  144.46  4970.4  137.57
  4995.9  137.57  5009.7  138.96  5096.4  136.41  5120.1  137.79  5136.2  141.97
  5232.7  157.19  5300.2  159.03  5319.4  161.45  5327.3  163.44  5344.2   171.2
  5395.1  199.41  5410.4  206.37  5441.1  212.82  5460.3  214.76  5475.9  214.71
#Mann= 6 ,-1 , 0
  4350.9     .06       0    4395     .11       0  4511.3     .15       0
  4795.2     .04       0  4860.2     .04       0  5136.2     .15       0
Bank Sta=4860.2,5136.2
XS Rating Curve= 0 ,0
Exp/Cntr=0.3,0.1

Type RM Length L Ch R = 1 ,8500    ,278,260,299
BEGIN DESCRIPTION:
SALUDA RIVER 20.0
END DESCRIPTION:
XS GIS Cut Line= 3
      1975275.11       793277.21      1975238.69       792601.99
      1975058.82       792003.85
#Sta/Elev= 30
  4323.8  181.73  4327.9  181.75  4480.3  168.37  4514.6  163.76    4544  162.32
  4564.5  158.56  4581.4  156.97  4677.6  155.47  4854.1  144.19  4888.2  142.51
  4904.1  140.19  4970.4   136.6  4995.9   136.6  5009.7  137.99  5096.4  135.44
  5120.1  136.82  5136.2     141    5175  143.91  5285.6  153.33  5390.5  155.29
  5461.3   158.5  5494.2  161.25  5503.3  163.35  5524.2   171.9  5559.2   190.5
  5568.4  193.04  5572.9  193.09  5588.6  199.08  5608.1  201.53  5624.6  201.77
#Mann= 5 ,-1 , 0
  4323.8     .06       0  4327.9     .11       0  4677.6     .04       0
  4854.1     .04       0    5175      .1       0
Bank Sta=4854.1,5175
XS Rating Curve= 0 ,0
Exp/Cntr=0.3,0.1

Type RM Length L Ch R = 1 ,8240    ,506,340,167
BEGIN DESCRIPTION:
SALUDA RIVER 19.0
END DESCRIPTION:
XS GIS Cut Line= 4
      1975561.45       793249.76      1975497.34        792576.8
      1975363.45       792162.28      1975183.71       791961.22
#Sta/Elev= 30
    4324  184.24  4356.6  182.41  4372.7  177.96    4395  178.93  4403.9  177.49
  4433.4   168.4    4479  166.82  4518.7  155.09  4530.1  154.08  4540.7  159.03
  4559.3  156.96  4569.9  150.42  4637.3  148.45    4800  143.71  4888.2     142
  4904.1  139.68  4970.4  136.09  5009.7  137.48  5096.4  134.93  5120.1  136.31
  5142.2   143.4    5495  150.15  5516.3  157.86  5529.4  156.89  5541.6  159.72
  5566.8  175.06  5626.8   182.8    5642  187.43  5676.4  189.57  5705.3  194.01
#Mann= 5 ,-1 , 0
    4324     .06       0  4403.9     .11       0  4637.3     .04       0
    4800     .04       0  5142.2     .15       0
Bank Sta=4800,5142.2
XS Rating Curve= 0 ,0
Exp/Cntr=0.3,0.1

Type RM Length L Ch R = 1 ,7900    ,486,500,550
BEGIN DESCRIPTION:
SALUDA RIVER 18.0
END DESCRIPTION:
XS GIS Cut Line= 3
      1976019.28       792850.52       1975821.7       792484.31
      1975193.71       791939.01
#Sta/Elev= 30
  4583.9  172.39  4599.9  173.64    4616  171.45  4632.8  163.95  4641.1  162.28
  4674.8  160.53  4702.2  151.89  4707.5  152.11  4740.3  144.31  4854.1  143.02
  4970.4  135.43  5009.7  136.82  5096.4  134.27  5120.1  135.65  5136.2  139.83
  5142.2  142.74  5148.1  145.64  5155.7  145.15  5183.1  147.89  5306.3  143.74
  5424.3  146.66  5582.5  146.58  5598.6  155.14  5620.2  163.08  5643.4  161.89
  5675.6  174.78  5699.5  177.24  5731.6   183.7  5792.8  189.13  5831.7  194.74
#Mann= 3 ,-1 , 0
  4583.9     .14       0  4740.3     .04       0  5142.2     .15       0
Bank Sta=4740.3,5142.2
XS Rating Curve= 0 ,0
Exp/Cntr=0.3,0.1

Type RM Length L Ch R = 1 ,7400    ,509,500,521
BEGIN DESCRIPTION:
SALUDA RIVER 17.0
END DESCRIPTION:
XS GIS Cut Line= 3
      1976384.47       792537.43      1976039.57       792046.83
      1975698.52       791635.28
#Sta/Elev= 30
  4400.3  177.51  4415.6  179.17    4430  177.07  4440.4  170.41  4483.4  163.55
  4514.6  163.89    4581   151.2  4628.8  145.98  4662.2  136.87  4711.4   137.4
  4854.1  141.62  4970.4  134.03  5009.7  135.42  5096.4  132.87  5120.1  134.25
  5142.2  141.34  5183.4  136.87  5255.8  146.26    5306  143.91  5334.7  145.56
  5365.3  150.51  5388.3  159.03  5404.7   162.6  5427.4  181.42  5444.6  193.98
  5452.2  197.29  5471.8  202.91  5515.4  211.69    5525  215.63  5534.5  216.52
#Mann= 6 ,-1 , 0
  4400.3     .14       0  4483.4     .11       0  4711.4     .04       0
  4854.1     .04       0  5142.2     .04       0  5255.8     .15       0
Bank Sta=4854.1,5142.2
XS Rating Curve= 0 ,0
Exp/Cntr=0.3,0.1

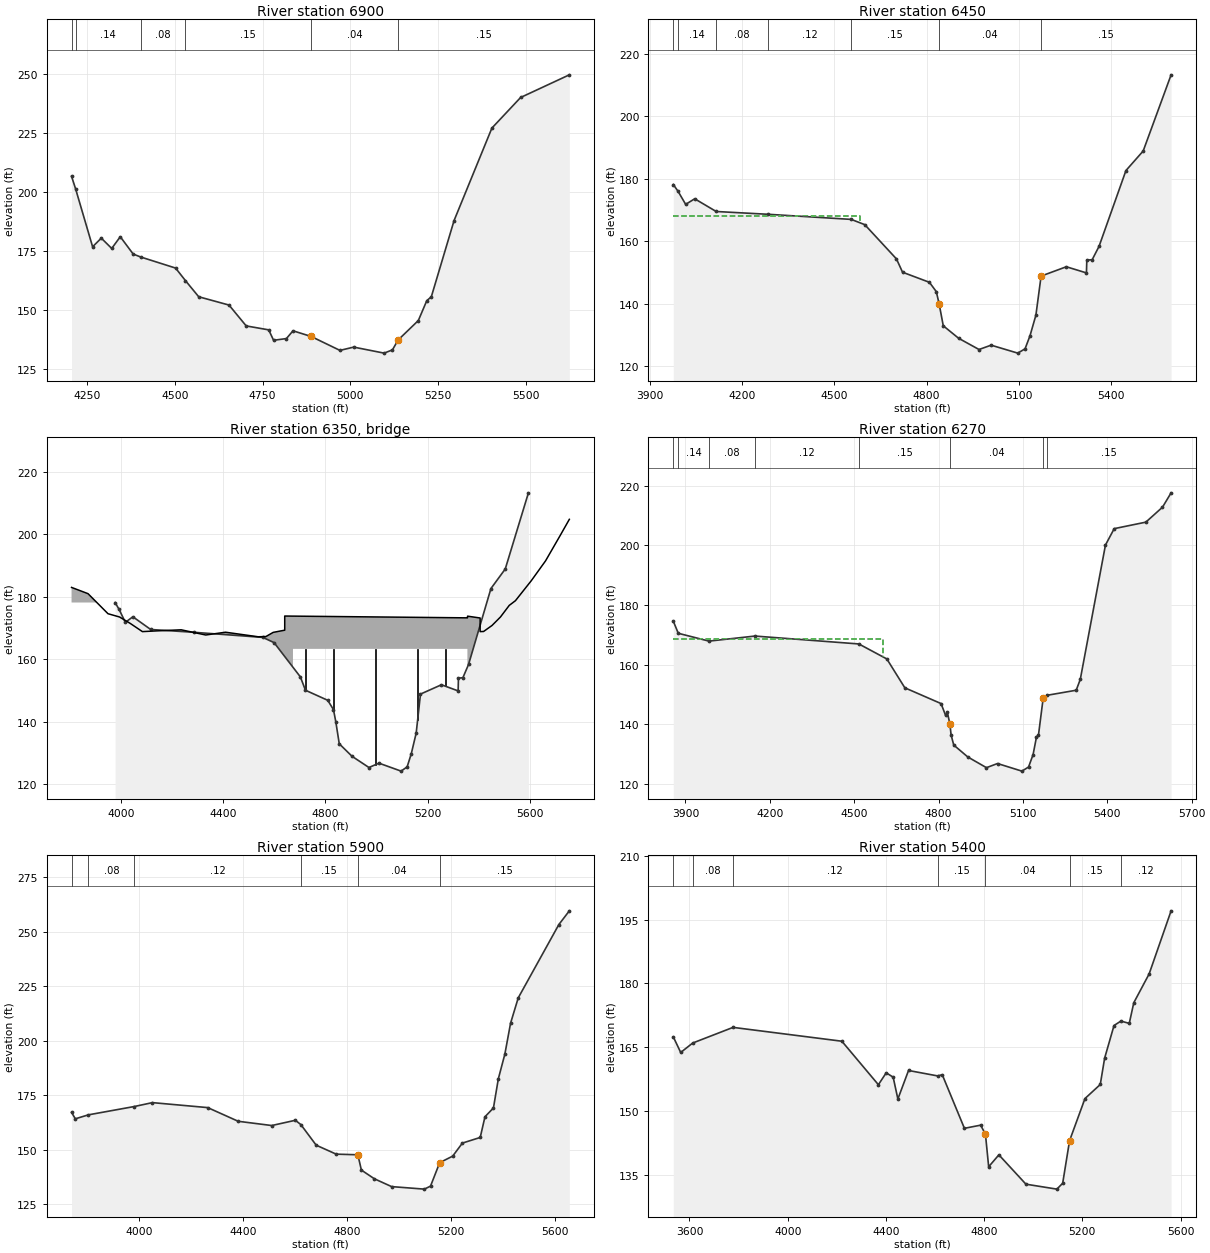
Type RM Length L Ch R = 1 ,6900    ,479,450,378
BEGIN DESCRIPTION:
SALUDA RIVER 16.0
END DESCRIPTION:
XS GIS Cut Line= 3
      1976827.42       792382.79      1976404.69       791709.85
      1976023.24       791215.51
#Sta/Elev= 30
  4205.3  206.79  4216.6   201.6  4265.3  176.95  4290.1   180.6  4319.8  176.24
  4344.2   181.2    4381  173.86  4402.2  172.62  4501.9  167.92  4529.7  162.65
  4567.8  155.76  4654.2  152.24  4703.2   143.4  4767.4  141.73  4781.2  137.31
  4817.8  138.04  4836.6  141.33  4888.2  138.94  4970.4  133.03  5009.7  134.42
  5096.4  131.87  5120.1  133.25  5136.2  137.43  5193.9  145.69    5218  154.11
  5230.9  155.74  5295.8  188.07  5403.6  227.25  5485.5  240.22  5624.4  249.82
#Mann= 6 ,-1 , 0
  4205.3     .06       0  4216.6     .14       0  4402.2     .08       0
  4529.7     .15       0  4888.2     .04       0  5136.2     .15       0
Bank Sta=4888.2,5136.2
XS Rating Curve= 0 ,0
Exp/Cntr=0.5,0.3

Type RM Length L Ch R = 1 ,6450    ,187,180,256
BEGIN DESCRIPTION:
SALUDA RIVER (Riverbanks Zoo - US)
END DESCRIPTION:
XS GIS Cut Line= 4
       1977292.9       792276.08      1977257.81       792069.43
      1976755.63       791428.17      1976269.39       791084.91
#Sta/Elev= 30
  3975.9  178.14  3991.4  175.95  4016.1  171.78  4045.5  173.57  4115.4   169.5
  4285.1   168.6  4554.6  166.97  4598.7  165.29  4701.8  154.32  4721.6  150.06
    4809  146.83  4831.4  143.85  4840.6  139.93  4854.1  132.91  4904.1  128.91
  4970.4  125.32  5009.7  126.71  5096.4  124.16  5120.1  125.54  5136.2  129.72
  5155.4  136.31  5172.3  148.82  5254.4  151.81  5319.8  149.84    5321  153.93
  5338.4  154.06  5360.7  158.32  5448.3  182.61  5504.4  188.87  5595.2  213.25
#Mann= 7 ,-1 , 0
  3975.9     .06       0  3991.4     .14       0  4115.4     .08       0
  4285.1     .12       0  4554.6     .15       0  4840.6     .04       0
  5172.3     .15       0
#XS Ineff= 2 , 0
       0  4582.8     168  5446.1       0  170.41
Permanent Ineff=
       F       F
Bank Sta=4840.6,5172.3
XS Rating Curve= 0 ,0
Exp/Cntr=0.5,0.3

Type RM Length L Ch R = 3 ,6350    ,,,
BEGIN DESCRIPTION:
SALUDA RIVER (Riverbanks Zoo - TOR)
Structure ID: R_SAL_01
Detailed Survey Structure
END DESCRIPTION:
Bridge Culvert--1,0,-1,-1, 0
Deck Dist Width WeirC Skew NumUp NumDn MinLoCord MaxHiCord MaxSubmerge Is_Ogee
90,20,3,0, 32, 32, , , 0.95, 0, 1,1,,
  3805.3  3869.8  3948.1  3993.4  4035.5  4082.9  4140.5  4234.9    4331  4408.5
  4536.4  4566.6  4595.3  4640.4  4640.4  4672.8  4672.8  5356.1  5356.1  5356.6
  5356.7    5406    5406  5419.5  5452.6  5485.5  5520.1  5544.2  5606.1  5662.2
  5720.9  5755.5
  182.97  180.97  174.55   173.5  171.43  168.82  169.06   169.4  167.74  168.63
  167.17  167.24  168.58  169.28  173.81  173.78  173.78  173.23  173.23  173.23
  173.77  173.18  168.82  168.86  170.79  173.49  177.22  178.71  185.09  191.46
  199.78  204.77
  104.16  104.16  104.16  104.16  104.16  104.16  104.16  104.16  104.16  104.16
  104.16  104.16  104.16  104.16  104.16  104.16   163.3   163.3  104.16  104.16
  104.16  104.16  104.16  104.16  104.16  104.16  104.16  104.16  104.16  104.16
  104.16  104.16
  3805.3  3869.8  3948.1  3993.4  4035.5  4082.9  4140.5  4234.9    4331  4408.5
  4536.4  4566.6  4595.3  4640.4  4640.4  4672.8  4672.8  5356.1  5356.1  5356.6
  5356.7    5406    5406  5419.5  5452.6  5485.5  5520.1  5544.2  5606.1  5662.2
  5720.9  5755.5
  182.97  180.97  174.55   173.5  171.43  168.82  169.06   169.4  167.74  168.63
  167.17  167.24  168.58  169.28  173.81  173.78  173.78  173.23  173.23  173.23
  173.77  173.18  168.82  168.86  170.79  173.49  177.22  178.71  185.09  191.46
  199.78  204.77
  104.16  104.16  104.16  104.16  104.16  104.16  104.16  104.16  104.16  104.16
  104.16  104.16  104.16  104.16  104.16  104.16   163.3   163.3  104.16  104.16
  104.16  104.16  104.16  104.16  104.16  104.16  104.16  104.16  104.16  104.16
  104.16  104.16
Pier Skew, UpSta & Num, DnSta & Num=  ,4721.6, 2 ,4721.6, 2 , 0 , 0 , 0 ,0,0
     2.5     2.5
  150.06   163.3
     2.5     2.5
  150.12   163.3
Pier Skew, UpSta & Num, DnSta & Num=  ,4831.4, 2 ,4831.4, 2 , 0 , 0 , 0 ,0,0
     2.5     2.5
  143.85   163.3
     2.5     2.5
  143.91   163.3
Pier Skew, UpSta & Num, DnSta & Num=  ,4995.9, 2 ,4995.9, 2 , 0 , 0 , 0 ,0,0
     2.5     2.5
  125.32   163.3
     2.5     2.5
  125.38   163.3
Pier Skew, UpSta & Num, DnSta & Num=  ,5161.1, 2 ,5161.1, 2 , 0 , 0 , 0 ,0,0
     2.5     2.5
  141.36   163.3
     2.5     2.5
  141.42   163.3
Pier Skew, UpSta & Num, DnSta & Num=  ,5271.2, 2 ,5271.2, 2 , 0 , 0 , 0 ,0,0
     2.5     2.5
  150.47   163.3
     2.5     2.5
  150.53   163.3
BR Coef= 1 , 1 , 0 ,1.25, 0 ,,,0.8,0,2,0,
WSPro=,,,, 1 ,,,, 0 ,,,, 0 ,,,,-1 ,-1 ,-1 , 0 , 0 , 0 , 0 , 0
BC Design=,, 0 ,, 0 ,,,,,,
BC HTab HWMax=213.25
BC Use User HTab Curves=0
BC User HTab FreeFlow(D)= 0

Type RM Length L Ch R = 1 ,6270    ,350,370,353
BEGIN DESCRIPTION:
SALUDA RIVER (Riverbanks Zoo - DS)
END DESCRIPTION:
XS GIS Cut Line= 4
        1977521.       792252.67      1977456.67       792007.05
      1976896.71       791316.44      1976509.18       790823.66
#Sta/Elev= 30
    3857  174.55  3874.6  170.48  3983.8  167.85  4147.4  169.55  4516.7   166.9
  4616.2  161.87  4680.2  152.18    4809  146.89  4825.1  142.92  4831.4  143.91
  4840.6  139.99  4844.6  136.38  4854.1  132.97  4904.1  128.97  4970.4  125.38
  5009.7  126.77  5096.4  124.22  5120.1   125.6  5136.2  129.78  5148.1  135.59
  5155.4  136.37  5172.3  148.88  5186.6  149.68  5289.5  151.37    5304  155.01
  5393.5   200.1  5424.6   205.6  5537.1  207.78  5596.3   212.8  5626.9  217.62
#Mann= 8 ,-1 , 0
    3857     .07       0  3874.6     .14       0  3983.8     .08       0
  4147.4     .12       0  4516.7     .15       0  4840.6     .04       0
  5172.3     .04       0  5186.6     .15       0
#XS Ineff= 2 , 0
       0  4602.8   168.7  5426.1       0  169.24
Permanent Ineff=
       F       F
Bank Sta=4840.6,5172.3
XS Rating Curve= 0 ,0
Exp/Cntr=0.5,0.3

Type RM Length L Ch R = 1 ,5900    ,475,500,577
BEGIN DESCRIPTION:
SALUDA RIVER 12.0
END DESCRIPTION:
XS GIS Cut Line= 3
      1977851.52       792172.26       1977193.9       791096.43
       1976744.6       790620.92
#Sta/Elev= 30
  3739.1  167.13  3753.6  164.17    3804  165.99  3980.4  169.81  4050.2   171.6
    4263  169.31  4380.2  163.03  4509.3  161.08  4600.1  163.49  4621.1  161.53
  4680.3  152.05  4757.2  147.94  4840.6  147.64  4854.1  140.62  4904.1  136.62
  4970.4  133.03  5096.4  131.87  5120.1  133.25  5155.4  144.02  5205.4  147.03
  5242.8  153.02  5311.3   155.6  5329.6  165.11  5362.2  169.15    5381  182.53
  5406.1  193.88  5428.1  208.09  5457.6  219.72  5613.8  253.38  5654.2  259.69
#Mann= 6 ,-1 , 0
  3739.1     .14       0    3804     .08       0  3980.4     .12       0
  4621.1     .15       0  4840.6     .04       0  5155.4     .15       0
Bank Sta=4840.6,5155.4
XS Rating Curve= 0 ,0
Exp/Cntr=0.3,0.1

Type RM Length L Ch R = 1 ,5400    ,412,500,635
BEGIN DESCRIPTION:
SALUDA RIVER 11.0
END DESCRIPTION:
XS GIS Cut Line= 4
      1977950.89       792189.73      1977743.74       791163.13
      1977578.28       790778.61       1977338.6       790270.61
#Sta/Elev= 30
  3534.1  167.46  3564.2   163.8  3613.2  166.02  3777.4  169.69  4220.7  166.44
  4369.4  156.23  4401.3  159.02  4429.6     158  4448.8  152.87  4492.2  159.57
  4610.2   158.3  4629.6  158.57  4719.8  145.99  4785.9  146.73  4805.5   144.6
  4818.6  136.96  4860.2  139.76  4970.4  132.87  5096.4  131.71  5120.1  133.09
  5148.1  143.08  5210.9  152.98  5273.2  156.28  5290.9  162.45  5329.2  170.13
  5357.2  171.17  5391.3  170.63  5409.7  175.48  5472.2  182.24  5561.7  197.06
#Mann= 7 ,-1 , 0
  3534.1     .14       0  3613.2     .08       0  3777.4     .12       0
  4610.2     .15       0  4805.5     .04       0  5148.1     .15       0
  5357.2     .12       0
Bank Sta=4805.5,5148.1
XS Rating Curve= 0 ,0
Exp/Cntr=0.3,0.1

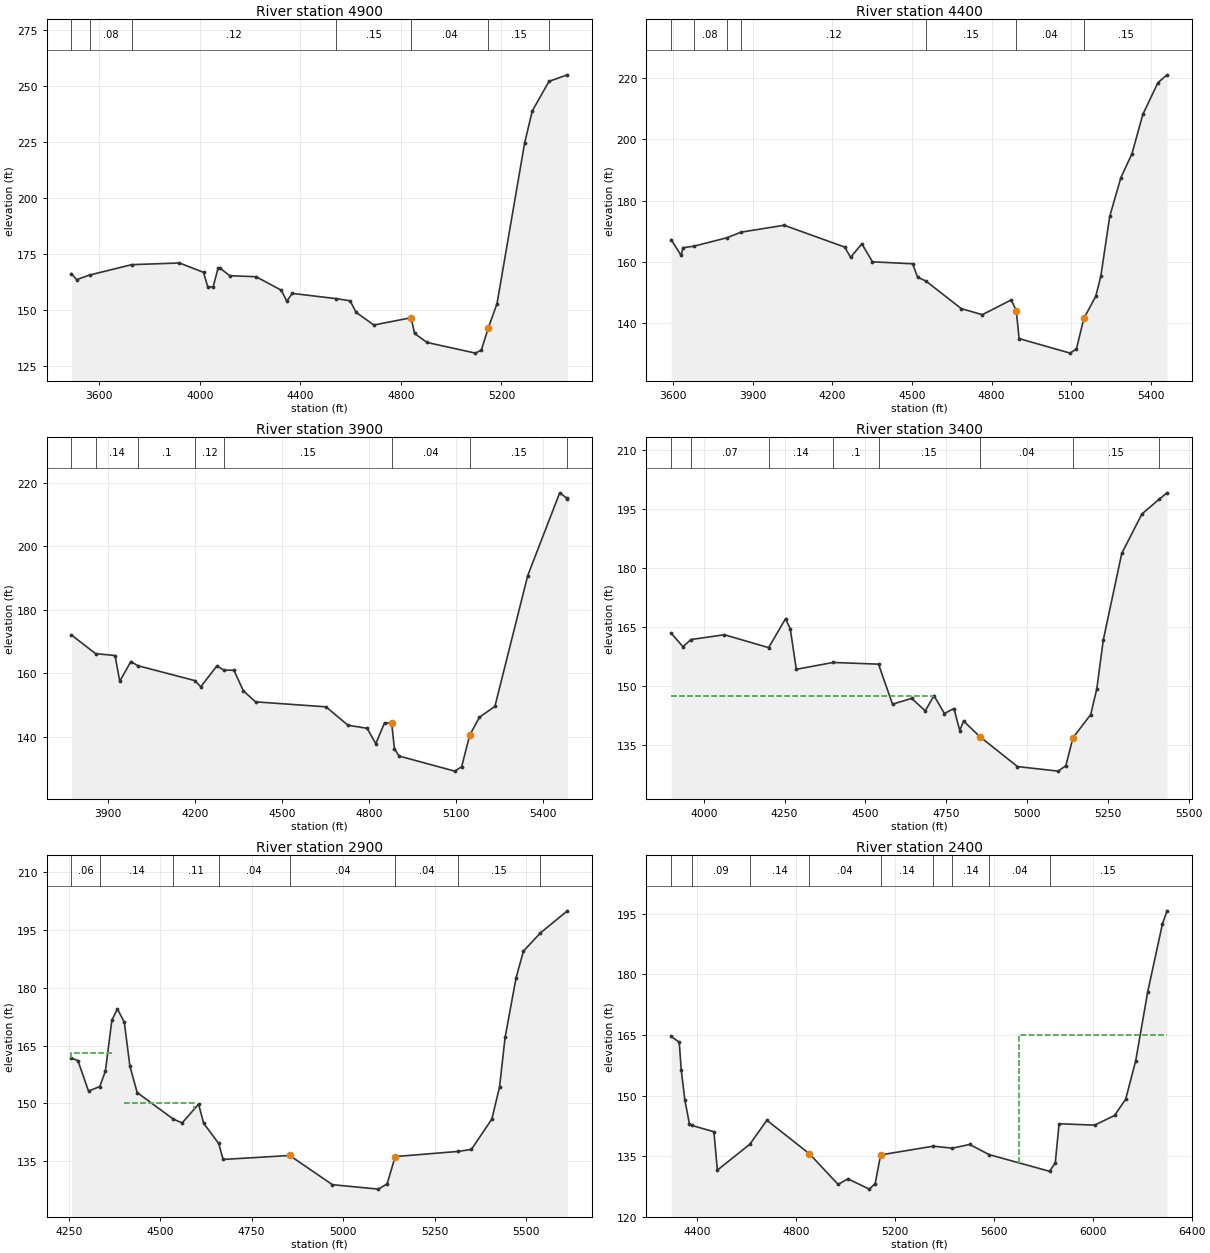
Type RM Length L Ch R = 1 ,4900    ,419,500,637
BEGIN DESCRIPTION:
SALUDA RIVER 10.0
END DESCRIPTION:
XS GIS Cut Line= 3
       1978001.9        792181.5      1978051.23        790671.1
      1978078.83       790209.63
#Sta/Elev= 30
  3488.8  166.33  3509.4  163.63  3560.9  165.69  3728.3  170.31  3918.4  171.07
  4014.3   166.9    4031  160.55  4052.4  160.33  4072.2  168.72  4080.1  168.77
  4118.5   165.4  4223.6  164.94  4324.2   158.9  4345.6  154.04  4367.5  157.51
  4542.2  155.18  4597.8  154.21  4621.5  149.07  4692.3  143.43  4840.6  146.67
  4854.1  139.65  4904.1  135.65  5096.4   130.9  5120.1  132.28  5148.1  142.27
  5182.4  152.96  5292.1  224.43  5322.6   238.8  5389.2  251.98  5462.3  254.89
#Mann= 7 ,-1 , 0
  3488.8     .14       0  3560.9     .08       0  3728.3     .12       0
  4542.2     .15       0  4840.6     .04       0  5148.1     .15       0
  5389.2     .12       0
Bank Sta=4840.6,5148.1
XS Rating Curve= 0 ,0
Exp/Cntr=0.3,0.1

Type RM Length L Ch R = 1 ,4400    ,514,500,484
BEGIN DESCRIPTION:
SALUDA RIVER 9.0
END DESCRIPTION:
XS GIS Cut Line= 4
      1978081.87       792189.71      1978292.06       791230.15
      1978500.08       790858.87      1978785.55         790496.
#Sta/Elev= 30
  3592.1  167.26  3629.8  162.04  3636.5  164.59  3678.2  165.09  3801.3  167.82
  3856.1  169.68    4018  171.94  4246.9  164.78  4268.6  161.42  4311.1  165.86
  4351.2  159.97  4502.4  159.33  4521.2  154.97  4552.7  153.67  4686.2  144.64
  4765.4  142.67  4874.5  147.51  4893.2  143.98  4904.1  134.84  5096.4  130.09
  5120.1  131.47  5148.1  141.46    5193  148.69    5212  155.23  5245.6  174.84
  5287.7  187.52  5329.6  195.37  5370.5  208.22  5427.4  218.59  5461.7  221.16
#Mann= 7 ,-1 , 0
  3592.1     .14       0  3678.2     .08       0  3801.3      .1       0
  3856.1     .12       0  4552.7     .15       0  4893.2     .04       0
  5148.1     .15       0
Bank Sta=4893.2,5148.1
XS Rating Curve= 0 ,0
Exp/Cntr=0.3,0.1

Type RM Length L Ch R = 1 ,3900    ,545,500,485
BEGIN DESCRIPTION:
SALUDA RIVER 8.0
END DESCRIPTION:
XS GIS Cut Line= 3
      1978348.12       792311.51      1978863.56       791199.24
       1979100.5       790776.28
#Sta/Elev= 30
  3774.1  172.08  3857.2  166.23  3924.5  165.62  3940.6  157.53    3979  163.74
    4003  162.43  4199.7  157.74  4220.1   155.8  4275.6  162.33  4300.8  161.01
  4334.5  161.02    4367  154.53  4409.2  151.06  4652.2  149.49  4727.9   143.7
  4794.1  142.74  4823.9  137.88  4854.1  144.48  4878.8  144.36  4888.2  136.34
  4904.1  134.02  5096.4  129.27  5120.1  130.65  5148.1  140.64  5181.6  146.23
  5234.9  149.64    5348  190.75  5458.4  216.79  5483.6  215.08  5484.8  214.97
#Mann= 8 ,-1 , 0
  3774.1     .07       0  3857.2     .14       0    4003      .1       0
  4199.7     .12       0  4300.8     .15       0  4878.8     .04       0
  5148.1     .15       0  5483.6     .11       0
Bank Sta=4878.8,5148.1
XS Rating Curve= 0 ,0
Exp/Cntr=0.3,0.1

Type RM Length L Ch R = 1 ,3400    ,568,500,286
BEGIN DESCRIPTION:
SALUDA RIVER 7.0
END DESCRIPTION:
XS GIS Cut Line= 3
      1979024.36       792530.86      1979286.73       791461.47
      1979423.42        791050.4
#Sta/Elev= 30
  3898.9  163.48  3935.5  160.04  3960.1  161.86  4063.8  163.07  4200.6   159.8
  4252.8  167.14  4267.6  164.53  4286.1   154.3  4400.1  156.04  4540.5  155.61
  4583.8  145.45  4643.1  146.92  4685.2  143.75    4712  147.62  4744.5  143.08
  4773.8  144.35    4792  138.75  4803.5  141.18  4854.1  137.21  4970.4  129.62
  5096.4  128.46  5120.1  129.84  5142.2  136.93  5197.1  142.83    5216  149.41
  5235.7  161.63    5293  183.71  5355.5  193.72  5409.6  197.51  5433.2  199.09
#Mann= 8 ,-1 , 0
  3898.9     .06       0  3960.1     .07       0  4200.6     .14       0
  4400.1      .1       0  4540.5     .15       0  4854.1     .04       0
  5142.2     .15       0  5409.6     .11       0
#XS Ineff= 2 , 0
       0    4710  147.65               0
Permanent Ineff=
       F       F
Bank Sta=4854.1,5142.2
XS Rating Curve= 0 ,0
Exp/Cntr=0.3,0.1

Type RM Length L Ch R = 1 ,2900    ,561,500,633
BEGIN DESCRIPTION:
SALUDA RIVER 6.0
END DESCRIPTION:
XS GIS Cut Line= 3
      1979870.59       792271.95      1979751.35       791539.18
      1979474.64       790992.64
#Sta/Elev= 30
  4257.6  161.67  4275.2   161.1  4304.2  153.15  4334.9  154.33  4350.3  158.33
    4368  171.59  4383.1  174.51    4402  171.06  4417.2  159.69  4437.1  152.77
  4535.7  145.87  4560.2  144.88  4604.9  149.74  4618.9  144.76    4660  139.52
  4671.9  135.37  4854.1   136.4  4970.4  128.81  5096.4  127.65  5120.1  129.03
  5142.2  136.12  5314.5  137.46  5350.3  137.97  5406.3  145.88  5427.3  154.22
  5442.5  167.15  5472.5  182.61  5492.5  189.53  5538.3  194.22  5612.6  200.03
#Mann= 8 ,-1 , 0
  4257.6     .06       0  4334.9     .14       0  4535.7     .11       0
    4660     .04       0  4854.1     .04       0  5142.2     .04       0
  5314.5     .15       0  5538.3     .11       0
#XS Ineff= 2 ,-1
    4250    4370     163    4400  4592.3  150.15
Permanent Ineff=
       F       F
Bank Sta=4854.1,5142.2
XS Rating Curve= 0 ,0
Exp/Cntr=0.3,0.1

Type RM Length L Ch R = 1 ,2400    ,496,400,119
BEGIN DESCRIPTION:
SALUDA RIVER 5.0
END DESCRIPTION:
XS GIS Cut Line= 3
      1980512.75       792074.32      1980236.87       791425.43
      1979505.82       790349.97
#Sta/Elev= 30
  4294.9  164.63  4327.6  163.22  4335.8  156.33  4350.3  148.93  4368.6  143.08
  4378.5  142.61    4468  141.04  4481.8  131.54  4613.2  137.95  4682.1  143.89
  4854.1  135.59  4970.4     128  5009.7  129.39  5096.4  126.84  5120.1  128.22
  5142.2  135.31  5354.8  137.47  5432.1  136.98  5502.2   137.9  5580.6  135.39
  5825.4  131.25  5848.4  133.36  5863.8  143.02  6007.7  142.68  6088.1  145.07
  6133.3  149.12  6173.6   158.6  6222.2  175.65  6281.5   192.4  6300.4  195.72
#Mann= 9 ,-1 , 0
  4294.9     .06       0  4378.5     .09       0  4613.2     .14       0
  4854.1     .04       0  5142.2     .14       0  5354.8     .04       0
  5432.1     .14       0  5580.6     .04       0  5825.4     .15       0
#XS Ineff= 2 , 0
       0                    5700       0     165
Permanent Ineff=
       F       F
Bank Sta=4854.1,5142.2
XS Rating Curve= 0 ,0
Exp/Cntr=0.3,0.1

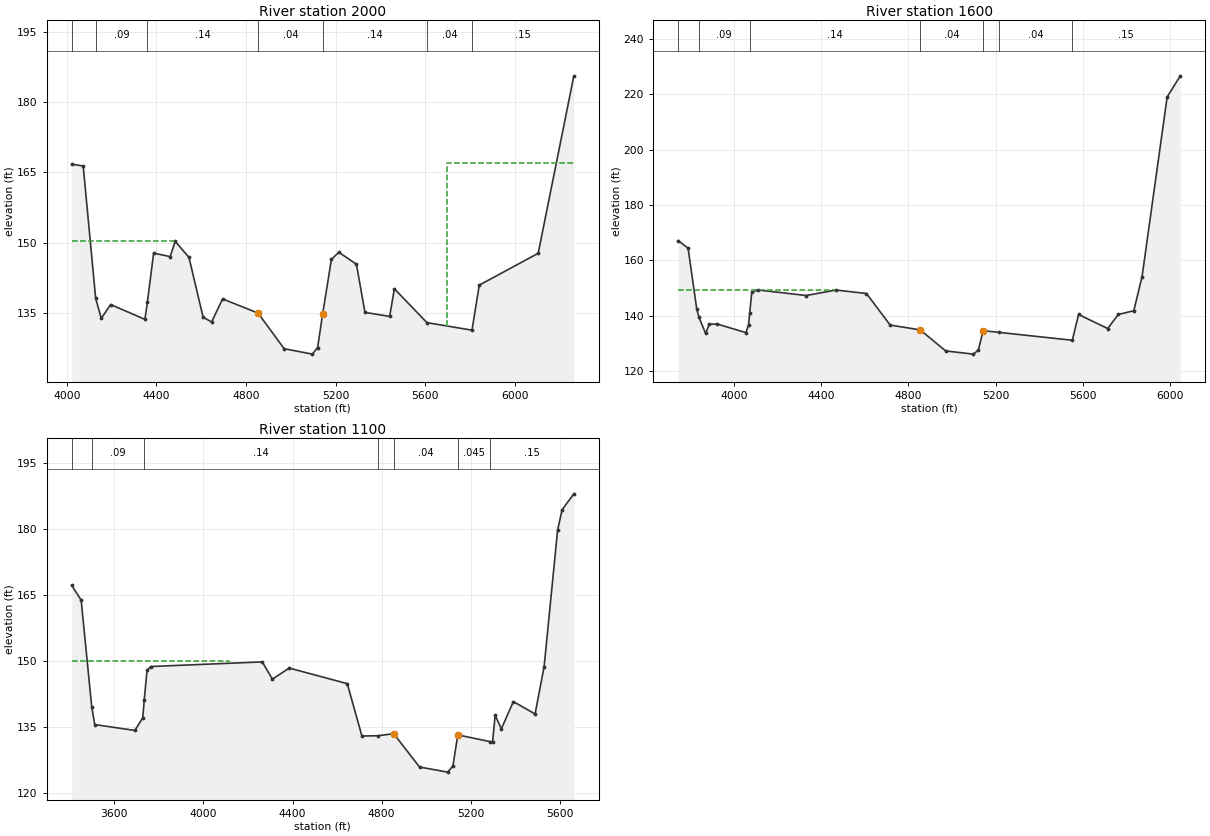
Type RM Length L Ch R = 1 ,2000    ,391,400,436
BEGIN DESCRIPTION:
SALUDA RIVER 4.0
END DESCRIPTION:
XS GIS Cut Line= 4
      1980926.55       791962.41      1980871.77       791502.24
      1980503.74       791141.86      1979525.11       790340.31
#Sta/Elev= 30
  4021.5  166.73  4072.6  166.31  4128.3  138.09  4153.3  133.81  4195.1  136.77
  4348.4  133.61  4359.7  137.36  4387.3  147.74  4461.4  146.99  4483.6  150.26
  4545.2  146.83  4608.3  134.07  4646.5  133.05  4695.4  137.97  4854.1  134.94
  4970.4  127.35  5096.4  126.19  5120.1  127.57  5142.2  134.66  5181.7  146.39
  5214.8  147.93  5293.6  145.36  5331.6   135.1  5441.9  134.23  5463.1  140.13
  5608.4  132.91  5809.8   131.3  5842.4  140.91  6105.7   147.7    6265  185.56
#Mann= 7 ,-1 , 0
  4021.5     .06       0  4128.3     .09       0  4359.7     .14       0
  4854.1     .04       0  5142.2     .14       0  5608.4     .04       0
  5809.8     .15       0
#XS Ineff= 2 , 0
       0  4483.6   150.3    5700       0     167
Permanent Ineff=
       F       F
Bank Sta=4854.1,5142.2
XS Rating Curve= 0 ,0
Exp/Cntr=0.3,0.1

Type RM Length L Ch R = 1 ,1600    ,406,500,615
BEGIN DESCRIPTION:
SALUDA RIVER 3.0
END DESCRIPTION:
XS GIS Cut Line= 4
      1980974.03       791933.21      1980911.94       791085.89
      1980656.51       790772.36      1979880.37       790072.62
#Sta/Elev= 30
    3746  167.18  3791.2  164.42  3830.6  142.56  3840.4  139.56  3871.4  133.64
  3888.2  136.98  3923.8  137.07    4056  133.95  4068.1  136.85  4073.3  141.01
  4082.9  148.68  4113.3  149.33  4332.1  147.35  4468.4  149.33    4608  148.07
  4716.5  136.68  4854.1  134.94  4970.4  127.35  5096.4  126.19  5120.1  127.57
  5142.2  134.66  5212.6  134.06  5550.6   131.2  5579.1   140.5  5712.5  135.44
  5760.9   140.5  5832.1  141.86  5869.9  154.17  5984.7  219.01    6045  226.66
#Mann= 7 ,-1 , 0
    3746     .06       0  3840.4     .09       0  4073.3     .14       0
  4854.1     .04       0  5142.2     .14       0  5212.6     .04       0
  5550.6     .15       0
#XS Ineff= 2 , 0
       0  4468.4  149.35               0
Permanent Ineff=
       F       F
Bank Sta=4854.1,5142.2
XS Rating Curve= 0 ,0
Exp/Cntr=0.3,0.1

Type RM Length L Ch R = 1 ,1100    ,576,500,474
BEGIN DESCRIPTION:
SALUDA RIVER 2.0
END DESCRIPTION:
XS GIS Cut Line= 4
      1980988.64       791922.27      1980963.07       790735.28
      1980895.99       790336.75      1980526.61       789785.94
#Sta/Elev= 30
  3408.6  167.18  3450.8  163.84  3498.1   139.6  3511.8  135.51    3692  134.18
  3727.4  137.06  3733.9  141.06  3746.6  147.86  3763.7  148.73  4263.8  149.78
  4309.6  145.86  4385.2  148.38  4645.7  144.83  4711.5  132.91  4783.3  132.97
  4854.1  133.44  4970.4  125.85  5096.4  124.69  5120.1  126.07  5142.2  133.16
  5285.6  131.65  5298.1  131.52  5309.9  137.61  5337.7  134.55  5391.6  140.75
  5489.1  137.92  5529.8  148.73  5590.2  179.73  5610.5  184.43  5663.2  188.04
#Mann= 7 ,-1 , 0
  3408.6     .06       0  3498.1     .09       0  3733.9     .14       0
  4783.3    .045       0  4854.1     .04       0  5142.2    .045       0
  5285.6     .15       0
#XS Ineff= 2 , 0
       0  4112.5   149.9               0
Permanent Ineff=
       F       F
Bank Sta=4854.1,5142.2
XS Rating Curve= 0 ,0
Exp/Cntr=0.3,0.1
LCMann Table=0

Chan Stop Cuts=-1
Use User Specified Reach Order=0
Composite Channel Slope=5

--- CCR_Prelim_Updated.g01 (geometry) ---

Geom Title=Existing Conditions
Program Version=5.03

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
River Reach=SALUDA RIVER    ,Reach-1

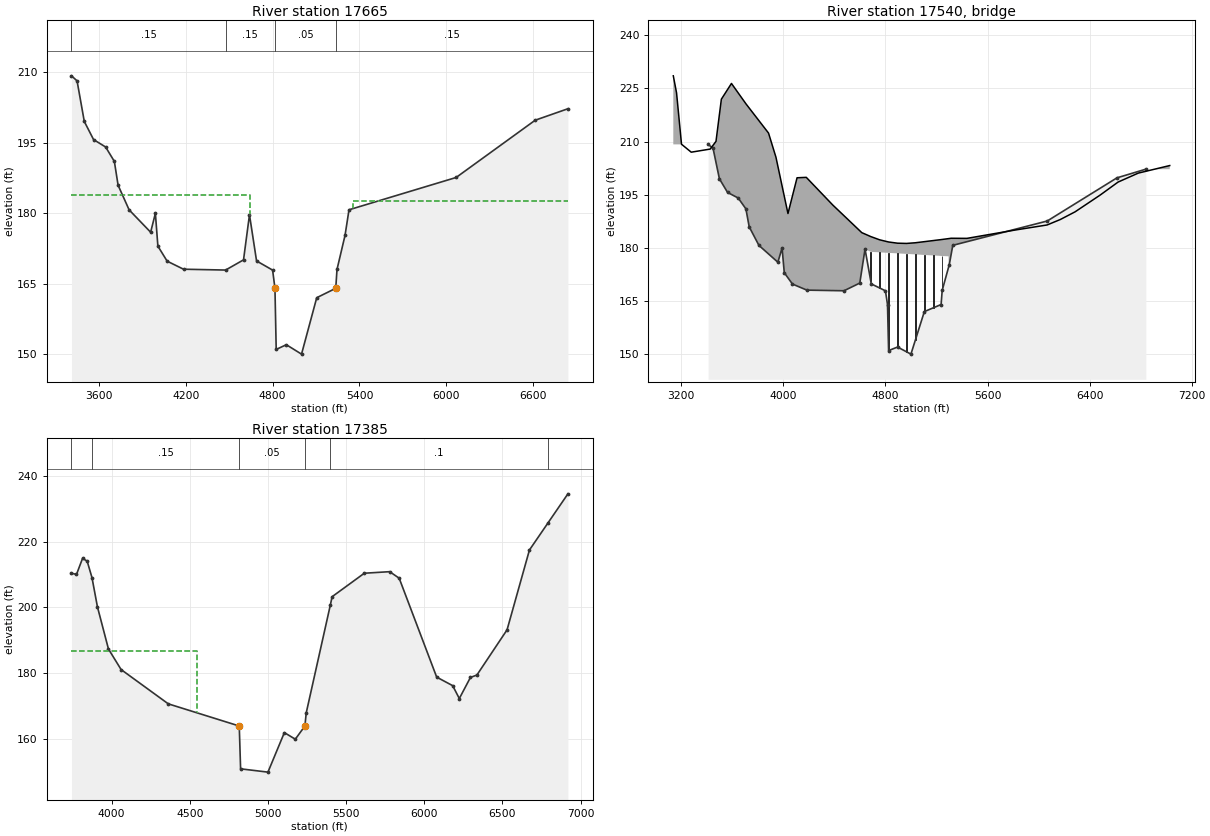
Type RM Length L Ch R = 1 ,17665   ,289,280,372
BEGIN DESCRIPTION:
SALUDA RIVER (I-26 - US)
END DESCRIPTION:
XS GIS Cut Line= 3
      1968995.05       798471.57      1968545.83       796947.19
      1967921.81       795215.91
#Sta/Elev= 30
  3410.8  209.19  3449.3  208.12  3499.3  199.48  3563.3  195.63  3646.7  194.05
  3706.9  190.99  3732.8  185.92    3809  180.68  3957.6  175.93  3990.3  179.95
  4007.6  172.97  4071.7  169.77  4184.8  168.06  4475.5  167.88  4599.3  170.05
  4640.4  179.64  4689.3  169.82  4800.2  167.87  4816.4     164    4825     151
    4895     152    5000     150    5105     162  5236.4     164    5245     168
  5300.6  175.27    5328   180.7    6068  187.57  6614.2  199.75  6840.3  202.19
#Mann= 4 ,-1 , 0
  3410.8     .15       0  4475.5     .15       0  4816.4     .05       0
  5236.4     .15       0
#XS Ineff= 2 , 0
       0  4641.5  183.88  5356.5       0  182.67
Permanent Ineff=
       F       F
Bank Sta=4816.4,5236.4
XS Rating Curve= 0 ,0
Exp/Cntr=0.5,0.3

Type RM Length L Ch R = 3 ,17540   ,,,
BEGIN DESCRIPTION:
SALUDA RIVER (I-26 - TOR)
Structure ID: I-26
Detailed Survey Structure
END DESCRIPTION:
Bridge Culvert--1,0,-1,-1, 0
Deck Dist Width WeirC Skew NumUp NumDn MinLoCord MaxHiCord MaxSubmerge Is_Ogee
61.5,127,3,0, 39, 39, , , 0.95, 0, 1,1,,
  3138.1  3163.5  3202.5  3278.6  3427.1  3472.6  3514.7  3593.8  3707.5  3884.3
  3942.5  4036.5  4107.7  4180.1  4387.1    4615    4635    4635    4685    4755
    4825    4895    4965    5035    5105    5175    5245    5295    5295    5315
  5438.9  5814.8  6066.9  6170.9  6286.3  6482.2  6623.1  6781.7  7027.8
  228.54  223.76  209.23  206.99  207.87  210.05  221.95  226.39  220.63  212.38
  205.56  189.68  199.77  199.89   192.1  184.28  183.97  183.97  183.18  182.26
  181.65  181.31  181.24  181.43  181.74  182.05  182.36   182.6   182.6   182.7
  182.67  185.01  186.45     188  190.16  194.88  198.56  201.09  203.22
     130     130     130     130     130     130     130     130     130     130
     130     130     130     130     130     130     130  178.97  178.87  178.72
  178.58  178.43  178.29  178.14  177.99  177.85   177.7   177.6     130     130
     130     130     130     130     130     130     130     130     130
  3138.1  3163.5  3202.5  3278.6  3427.1  3472.6  3514.7  3593.8  3707.5  3884.3
  3942.5  4036.5  4107.7  4180.1  4387.1    4615    4635    4635    4685    4755
    4825    4895    4965    5035    5105    5175    5245    5295    5295    5315
  5438.9  5814.8  6066.9  6170.9  6286.3  6482.2  6623.1  6781.7  7027.8
  228.54  223.76  209.23  206.99  207.87  210.05  221.95  226.39  220.63  212.38
  205.56  189.68  199.77  199.89   192.1  184.28  183.97  183.97  183.18  182.26
  181.65  181.31  181.24  181.43  181.74  182.05  182.36   182.6   182.6   182.7
  182.67  185.01  186.45     188  190.16  194.88  198.56  201.09  203.22
     130     130     130     130     130     130     130     130     130     130
     130     130     130     130     130     130     130  178.97  178.87  178.72
  178.58  178.43  178.29  178.14  177.99  177.85   177.7   177.6     130     130
     130     130     130     130     130     130     130     130     130
Pier Skew, UpSta & Num, DnSta & Num=  ,4685, 2 ,4685, 2 , 0 , 0 , 0 ,0,0
       4       4
   163.5  178.86
       4       4
   163.5  178.86
Pier Skew, UpSta & Num, DnSta & Num=  ,4755, 2 ,4755, 2 , 0 , 0 , 0 ,0,0
       4       4
     163  178.72
       4       4
     163  178.72
Pier Skew, UpSta & Num, DnSta & Num=  ,4825, 2 ,4825, 2 , 0 , 0 , 0 ,0,0
       4       4
     149  178.57
       4       4
     149  178.57
Pier Skew, UpSta & Num, DnSta & Num=  ,4895, 2 ,4895, 2 , 0 , 0 , 0 ,0,0
       4       4
     150  178.43
       4       4
     150  178.43
Pier Skew, UpSta & Num, DnSta & Num=  ,4965, 2 ,4965, 2 , 0 , 0 , 0 ,0,0
       4       4
   148.5  178.28
       4       4
   148.5  178.28
Pier Skew, UpSta & Num, DnSta & Num=  ,5035, 2 ,5035, 2 , 0 , 0 , 0 ,0,0
       4       4
     153  178.14
       4       4
     153  178.14
Pier Skew, UpSta & Num, DnSta & Num=  ,5105, 2 ,5105, 2 , 0 , 0 , 0 ,0,0
       4       4
     160     178
       4       4
     160     178
Pier Skew, UpSta & Num, DnSta & Num=  ,5175, 2 ,5175, 2 , 0 , 0 , 0 ,0,0
       4       4
     158  177.85
       4       4
     158  177.85
Pier Skew, UpSta & Num, DnSta & Num=  ,5245, 2 ,5245, 2 , 0 , 0 , 0 ,0,0
       4       4
     166  177.71
       4       4
     166  177.71
BR Coef= 1 , 0 , 0 ,1.25, 0 ,,,0.8,0,2,0,
WSPro=,,,, 1 ,,,, 0 ,,,, 0 ,,,,-1 ,-1 ,-1 , 0 , 0 , 0 , 0 , 0
BC Design=,, 0 ,, 0 ,,,,,,
BC HTab HWMax=209.19
BC Use User HTab Curves=0
BC User HTab FreeFlow(D)= 0

Type RM Length L Ch R = 1 ,17385   ,306,385,416
BEGIN DESCRIPTION:
SALUDA RIVER (I-26 - DS)
END DESCRIPTION:
XS GIS Cut Line= 3
      1969350.99       798187.76      1968803.81         797056.
       1968156.7       795248.87
#Sta/Elev= 30
  3742.9  210.41  3774.9  210.03  3813.7  214.91  3843.2  214.07  3874.1  209.05
    3909  200.17  3979.5  187.38  4060.3  181.15  4362.4  170.73  4816.4     164
    4825     151    5000     150    5105     162    5175     160  5236.4     164
    5245     168  5399.2  200.73  5410.6  203.27  5616.7   210.4  5778.9  210.87
  5839.7  208.89  6079.7  178.85    6182  176.26  6224.5  172.35  6295.6  178.75
  6337.1  179.49    6530  193.21  6673.3  217.46    6793  225.75  6919.5  234.51
#Mann= 6 ,-1 , 0
  3742.9     .06       0  3874.1     .15       0  4816.4     .05       0
  5236.4     .15       0  5399.2      .1       0    6793     .11       0
#XS Ineff= 2 , 0
       0  4543.5  186.69  5386.5       0  182.42
Permanent Ineff=
       F       F
Bank Sta=4816.4,5236.4
XS Rating Curve= 0 ,0
Exp/Cntr=0.5,0.3

--- CCR_Prelim_Updated.g02 (geometry) ---

Geom Title=Ex_con_with added
Program Version=5.03

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
River Reach=SALUDA RIVER    ,Reach-1

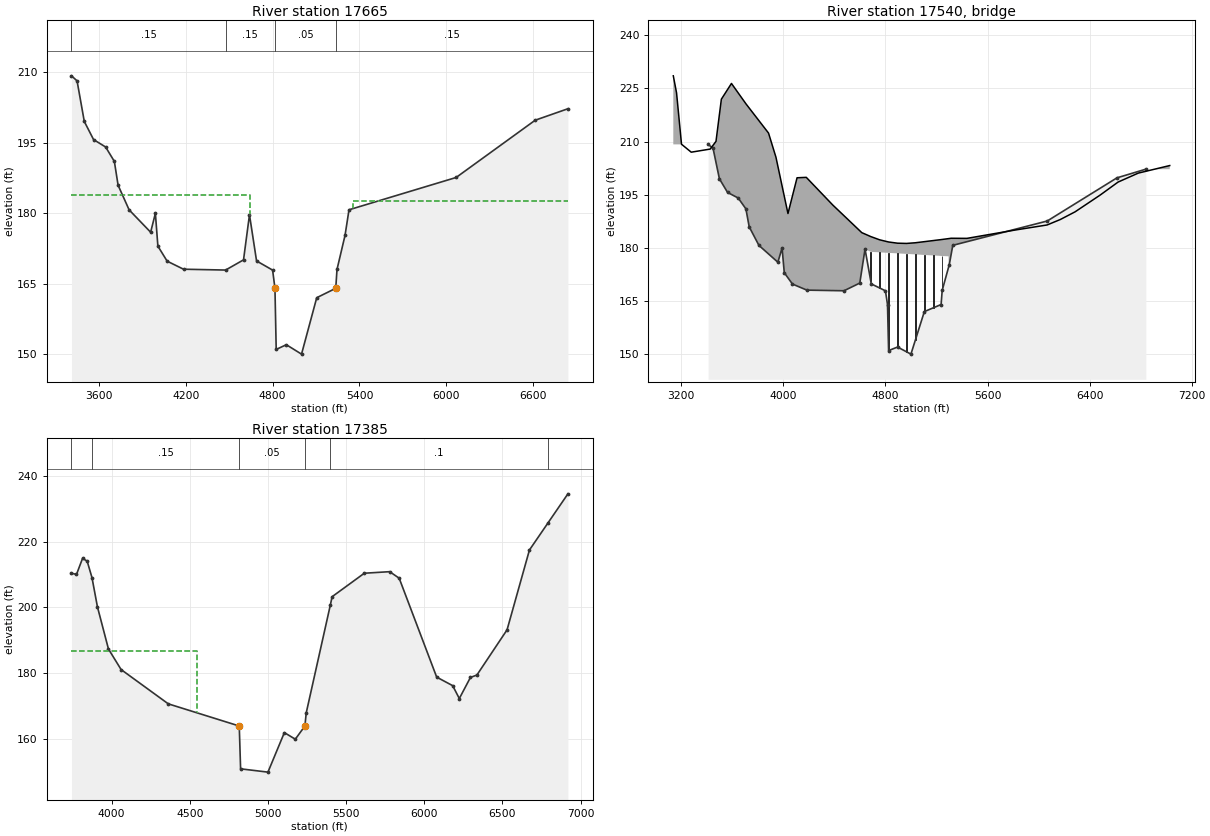
Type RM Length L Ch R = 1 ,17665   ,289,280,372
BEGIN DESCRIPTION:
SALUDA RIVER (I-26 - US)
END DESCRIPTION:
XS GIS Cut Line= 3
      1968995.05       798471.57      1968545.83       796947.19
      1967921.81       795215.91
#Sta/Elev= 30
  3410.8  209.19  3449.3  208.12  3499.3  199.48  3563.3  195.63  3646.7  194.05
  3706.9  190.99  3732.8  185.92    3809  180.68  3957.6  175.93  3990.3  179.95
  4007.6  172.97  4071.7  169.77  4184.8  168.06  4475.5  167.88  4599.3  170.05
  4640.4  179.64  4689.3  169.82  4800.2  167.87  4816.4     164    4825     151
    4895     152    5000     150    5105     162  5236.4     164    5245     168
  5300.6  175.27    5328   180.7    6068  187.57  6614.2  199.75  6840.3  202.19
#Mann= 4 ,-1 , 0
  3410.8     .15       0  4475.5     .15       0  4816.4     .05       0
  5236.4     .15       0
#XS Ineff= 2 , 0
       0  4641.5  183.88  5356.5       0  182.67
Permanent Ineff=
       F       F
Bank Sta=4816.4,5236.4
XS Rating Curve= 0 ,0
Exp/Cntr=0.5,0.3

Type RM Length L Ch R = 3 ,17540   ,,,
BEGIN DESCRIPTION:
SALUDA RIVER (I-26 - TOR)
Structure ID: I-26
Detailed Survey Structure
END DESCRIPTION:
Bridge Culvert--1,0,-1,-1, 0
Deck Dist Width WeirC Skew NumUp NumDn MinLoCord MaxHiCord MaxSubmerge Is_Ogee
61.5,127,3,0, 39, 39, , , 0.95, 0, 1,1,,
  3138.1  3163.5  3202.5  3278.6  3427.1  3472.6  3514.7  3593.8  3707.5  3884.3
  3942.5  4036.5  4107.7  4180.1  4387.1    4615    4635    4635    4685    4755
    4825    4895    4965    5035    5105    5175    5245    5295    5295    5315
  5438.9  5814.8  6066.9  6170.9  6286.3  6482.2  6623.1  6781.7  7027.8
  228.54  223.76  209.23  206.99  207.87  210.05  221.95  226.39  220.63  212.38
  205.56  189.68  199.77  199.89   192.1  184.28  183.97  183.97  183.18  182.26
  181.65  181.31  181.24  181.43  181.74  182.05  182.36   182.6   182.6   182.7
  182.67  185.01  186.45     188  190.16  194.88  198.56  201.09  203.22
     130     130     130     130     130     130     130     130     130     130
     130     130     130     130     130     130     130  178.97  178.87  178.72
  178.58  178.43  178.29  178.14  177.99  177.85   177.7   177.6     130     130
     130     130     130     130     130     130     130     130     130
  3138.1  3163.5  3202.5  3278.6  3427.1  3472.6  3514.7  3593.8  3707.5  3884.3
  3942.5  4036.5  4107.7  4180.1  4387.1    4615    4635    4635    4685    4755
    4825    4895    4965    5035    5105    5175    5245    5295    5295    5315
  5438.9  5814.8  6066.9  6170.9  6286.3  6482.2  6623.1  6781.7  7027.8
  228.54  223.76  209.23  206.99  207.87  210.05  221.95  226.39  220.63  212.38
  205.56  189.68  199.77  199.89   192.1  184.28  183.97  183.97  183.18  182.26
  181.65  181.31  181.24  181.43  181.74  182.05  182.36   182.6   182.6   182.7
  182.67  185.01  186.45     188  190.16  194.88  198.56  201.09  203.22
     130     130     130     130     130     130     130     130     130     130
     130     130     130     130     130     130     130  178.97  178.87  178.72
  178.58  178.43  178.29  178.14  177.99  177.85   177.7   177.6     130     130
     130     130     130     130     130     130     130     130     130
Pier Skew, UpSta & Num, DnSta & Num=  ,4685, 2 ,4685, 2 , 0 , 0 , 0 ,0,0
       4       4
   163.5  178.86
       4       4
   163.5  178.86
Pier Skew, UpSta & Num, DnSta & Num=  ,4755, 2 ,4755, 2 , 0 , 0 , 0 ,0,0
       4       4
     163  178.72
       4       4
     163  178.72
Pier Skew, UpSta & Num, DnSta & Num=  ,4825, 2 ,4825, 2 , 0 , 0 , 0 ,0,0
       4       4
     149  178.57
       4       4
     149  178.57
Pier Skew, UpSta & Num, DnSta & Num=  ,4895, 2 ,4895, 2 , 0 , 0 , 0 ,0,0
       4       4
     150  178.43
       4       4
     150  178.43
Pier Skew, UpSta & Num, DnSta & Num=  ,4965, 2 ,4965, 2 , 0 , 0 , 0 ,0,0
       4       4
   148.5  178.28
       4       4
   148.5  178.28
Pier Skew, UpSta & Num, DnSta & Num=  ,5035, 2 ,5035, 2 , 0 , 0 , 0 ,0,0
       4       4
     153  178.14
       4       4
     153  178.14
Pier Skew, UpSta & Num, DnSta & Num=  ,5105, 2 ,5105, 2 , 0 , 0 , 0 ,0,0
       4       4
     160     178
       4       4
     160     178
Pier Skew, UpSta & Num, DnSta & Num=  ,5175, 2 ,5175, 2 , 0 , 0 , 0 ,0,0
       4       4
     158  177.85
       4       4
     158  177.85
Pier Skew, UpSta & Num, DnSta & Num=  ,5245, 2 ,5245, 2 , 0 , 0 , 0 ,0,0
       4       4
     166  177.71
       4       4
     166  177.71
BR Coef= 1 , 1 , 0 ,1.25, 0 ,,,0.8,0,2,0,
WSPro=,,,, 1 ,,,, 0 ,,,, 0 ,,,,-1 ,-1 ,-1 , 0 , 0 , 0 , 0 , 0
BC Design=,, 0 ,, 0 ,,,,,,
BC HTab HWMax=209.19
BC Use User HTab Curves=0
BC User HTab FreeFlow(D)= 0

Type RM Length L Ch R = 1 ,17385   ,306,385,416
BEGIN DESCRIPTION:
SALUDA RIVER (I-26 - DS)
END DESCRIPTION:
XS GIS Cut Line= 3
      1969350.99       798187.76      1968803.81         797056.
       1968156.7       795248.87
#Sta/Elev= 30
  3742.9  210.41  3774.9  210.03  3813.7  214.91  3843.2  214.07  3874.1  209.05
    3909  200.17  3979.5  187.38  4060.3  181.15  4362.4  170.73  4816.4     164
    4825     151    5000     150    5105     162    5175     160  5236.4     164
    5245     168  5399.2  200.73  5410.6  203.27  5616.7   210.4  5778.9  210.87
  5839.7  208.89  6079.7  178.85    6182  176.26  6224.5  172.35  6295.6  178.75
  6337.1  179.49    6530  193.21  6673.3  217.46    6793  225.75  6919.5  234.51
#Mann= 6 ,-1 , 0
  3742.9     .06       0  3874.1     .15       0  4816.4     .05       0
  5236.4     .15       0  5399.2      .1       0    6793     .11       0
#XS Ineff= 2 , 0
       0  4543.5  186.69  5386.5       0  182.42
Permanent Ineff=
       F       F
Bank Sta=4816.4,5236.4
XS Rating Curve= 0 ,0
Exp/Cntr=0.5,0.3